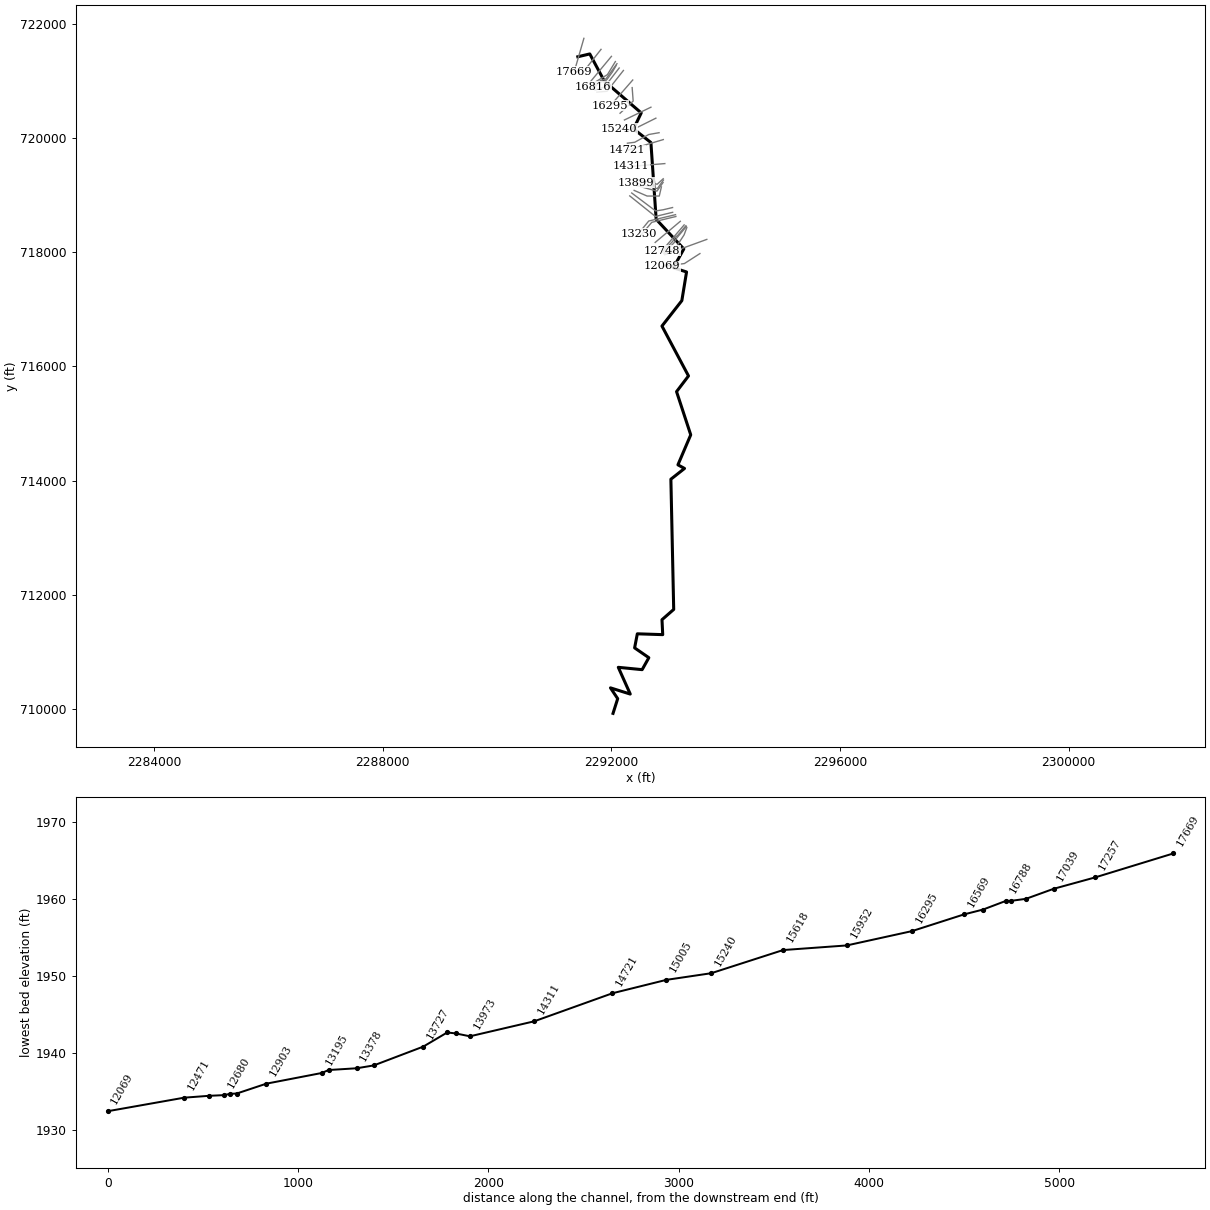
--- CLAYLCKRN.prj (project) ---

Proj Title=CLAYLCKRN
Current Plan=p01
Default Exp/Contr=0,0
English Units
Geom File=g01
Flow File=f01
Plan File=p01
BEGIN DESCRIPTION:
----------MODEL BY WOOD PLC 2022----------
AFH study
Randolph County, WV
HEC-RAS Version: RAS 6.2
Vertical Datum: NAVD88
Projection: NAD 1983 StatePlane West Virginia S FIPS 4702 (US Feet)
Terrain: 1-meter LIDAR (FEMA Region III 3DEP collected 2016-2018)
Land Use: 2019 NLCD
Hydrologic Method:
WV SIR2010-5033 regression equations
Additional Model Notes:
None
END DESCRIPTION:
DSS Export Rating Curves= 0
DSS Export Rating Curve Sorted= 0
DSS Export Volume Flow Curves= 0
DXF OffsetX= 0
DXF OffsetY= 0
DXF ScaleX= 0
DXF ScaleY= 0

--- CLAYLCKRN.p01 (plan) ---

Plan Title=Floodplain
Program Version=6.20
Short Identifier=Floodplain
Geom File=g01
Flow File=f01
Subcritical Flow
K Sum by GR= 0
Std Step Tol= 0.01
Critical Tol= 0.01
Num of Std Step Trials= 20
Max Error Tol= 0.3
Flow Tol Ratio= 0.001
Split Flow NTrial= 30
Split Flow Tol= 0.02
Split Flow Ratio= 0.02
Log Output Level= 0
Friction Slope Method= 1
Unsteady Friction Slope Method= 2
Unsteady Bridges Friction Slope Method= 1
Parabolic Critical Depth
Global Vel Dist= 0 , 0 , 0
Global Log Level= 0
CheckData=True
Encroach Param=-1 ,0,0, 0
Mapping Interval=1HOUR
Computation Time Step Use Courant=        0
Computation Time Step Use Time Series=    0
Computation Time Step Count To Double=0
Computation Time Step Max Doubling=0
Computation Time Step Max Halving=0
Computation Time Step Residence Courant=0
Run HTab= 0
Run UNet= 0
Run Sediment= 0
Run PostProcess= 0
Run WQNet= 0
Run RASMapper=-1
UNET Theta= 0
UNET Theta Warmup= 0
UNET ZTol= 0
UNET ZSATol= 0
UNET MxIter= 0
UNET Max Iter WO Improvement= 0
UNET MaxInSteps= 0
UNET DtIC= 0
UNET DtMin= 0
UNET MaxCRTS= 0
UNET WFStab= 0
UNET SFStab= 0
UNET WFX= 1
UNET SFX= 1
UNET Gravity=32.174
UNET 1D Methodology=Finite Difference
UNET DSS MLevel= 1
UNET Pardiso=0
UNET DZMax Abort= 0
UNET Use Existing IB Tables= 0
UNET Froude Reduction=False
UNET Froude Limit= 0
UNET Froude Power= 0
UNET D1 Cores= 0
UNET WindReference=Eulerian
UNET WindDragFormulation=Hsu (1988)
UNET D2 Coriolis=0
UNET D2 Cores= 0
UNET D2 Theta= 1
UNET D2 Theta Warmup= 1
UNET D2 Z Tol= 0.01
UNET D2 Volume Tol= 0.01
UNET D2 Max Iterations= 20
UNET D2 Equation= 0
UNET D2 RampUpFraction=0.1
UNET D2 TimeSlices= 1
UNET D2 Turbulence Formulation=Non-Conservative (original)
UNET D2 Eddy Viscosity=0.3
UNET D2 Transverse Eddy Viscosity=0.1
UNET D2 Smagorinsky Mixing=0
UNET D2 BCVolumeCheck=0
UNET D2 Cores=0
UNET D2 SolverType=PARDISO (Direct)
UNET D2 Minimum Iterations= 2147483647
UNET D2 Maximum Iterations= 2147483647
UNET D2 Restart Number= 10
UNET D2 Relaxation Coeff=1.3
UNET D2 SOR Precondition Iterations= 10
UNET D2 ILUT Maximum Fill= 8
UNET D2 ILUT Tolerance=1E-08
UNET D1D2 MaxIter= 0
UNET D1D2 ZTol=0.01
UNET D1D2 QTol=0.1
UNET D1D2 MinQTol=1
Write IC File= 0
Write IC File at Fixed DateTime=0
Write IC File at Sim End=0
Echo Input=False
Echo Parameters=False
Echo Output=False
Write Detailed= 0
HDF Write Warmup=0
HDF Write Time Slices=0
HDF Flush=0
HDF Compression= 1
HDF Chunk Size= 1
HDF Spatial Parts= 1
HDF Use Max Rows=0
HDF Fixed Rows= 1
Calibration Method= 0
Calibration Iterations= 20
Calibration Max Change=0.05
Calibration Tolerance=0.2
Calibration Maximum=1.5
Calibration Minimum=0.5
Calibration Optimization Method= 1
WQ AD Non Conservative
WQ ULTIMATE=-1
WQ Max Comp Step=1HOUR
WQ Output Interval=15MIN
WQ Output Selected Increments= 0
WQ Output face flow=0
WQ Output face velocity=0
WQ Output face area=0
WQ Output face dispersion=0
WQ Output cell volume=0
WQ Output cell surface area=0
WQ Output cell continuity=0
WQ Output cumulative cell continuity=0
WQ Output face conc=0
WQ Output face dconc_dx=0
WQ Output face courant=0
WQ Output face peclet=0
WQ Output face adv mass=0
WQ Output face disp mass=0
WQ Output cell mass=0
WQ Output cell source sink temp=0
WQ Output nsm pathways=0
WQ Output nsm derived pathways=0
WQ Create Restart=0
WQ Fixed Restart=0
WQ System Summary=0
WQ Write To DSS=0
Sorting and Armoring Iterations= 10
XS Update Threshold= 0.02
Bed Roughness Predictor= 0
Hydraulics Update Threshold= 0.02
Energy Slope Method= 1
Volume Change Method= 1
Sediment Retention Method= 0
Sediment TS Multiplier= 1
Warm Up Method= 0
XS Weighting Method= 0
Number of US Weighted Cross Sections= 1
Number of DS Weighted Cross Sections= 1
Upstream XS Weight=0
Main XS Weight=1
Downstream XS Weight=0
Number of DS XS's Weighted with US Boundary= 1
Upstream Boundary Weight= 1
Weight of XSs Associated with US Boundary= 0
Number of US XS's Weighted with DS Boundary= 1
Downstream Boundary Weight= 0.5
Weight of XSs Associated with DS Boundary= 0.5
Percentile Method= 0
Sediment Output Level= 3
Mass or Volume Output= 0
Output Increment Type= 1
Profile and TS Output Increment= 1
Transport Output Increment 1
XS Output Flag= 0
XS Output Increment= 10
Read HDF5 Sediment Hotstart= 0
Sediment Hotstart Type= 0
Write Gradation File= 0
Read Gradation Hotstart= 0
Write HDF5 File= 1
Write Binary Output= 1
Write DSS Sediment File= 0
DSS Sediment Output Type= 1
SV Curve= 0
Specific Gage Flag= 0
Subcell Erosion Methods= 0
Subcell Deposition Methods= 0
Advection Scheme= 1
Matrix Solver= 0
Implicit Weighting Factor= 1
Maximum Outer Loop Convergence Iterations= 5
Convergence Maximum Absolute= 0.001
Convergence RMSE= 0.0001
Grain Fractions Max Abs Error= 0.001
Max Subgrid Regions= 1
Max Subgrid Length Scale= 3.402823E+38
Initial Layer Thickness= 3.402823E+38
Min Layer Thickness= 3.402823E+38
Max Layer Thickness= 3.402823E+38
Number of Layers= 5

--- CLAYLCKRN.f01 (steady flow) ---

Flow Title=Flow
Program Version=6.20
Number of Profiles= 1
Profile Names=P100yr
River Rch & RM=CLAYLCKRN,Main,17669
     518
River Rch & RM=CLAYLCKRN,Main,13468
     808
River Rch & RM=CLAYLCKRN,Main,9831
     904
River Rch & RM=CLAYLCKRN,Main,5933
    1170
Boundary for River Rch & Prof#=CLAYLCKRN,Main            , 1
Up Type= 0
Dn Type= 3
Dn Slope=0.00144
DSS Import GetInterval= 0
DSS Import GetPeak= 0
DSS Import FillOption= 0

--- CLAYLCKRN.g01 (geometry) ---

Geom Title=Geometry
Program Version=6.20

River Reach=CLAYLCKRN       ,Main
Reach XY= 30
     2291412.909      721420.779     2291622.111      721470.258
     2291876.645      720995.454     2292522.243      720437.794
     2292388.453      720158.157     2292691.555      719919.043
     2292783.657      718575.045     2293267.375      718056.177
     2293085.355      717726.666     2293315.194      717653.137
     2293232.696      717151.019     2292884.842      716705.859
     2293349.255      715832.708     2293140.287      715557.904
     2293388.318      714801.458      2293164.36      714276.284
     2293279.811      714212.916     2293041.096      714024.548
     2293090.393      711744.398      2292885.44      711564.559
     2292898.238      711303.201     2292453.967      711317.784
     2292406.572       711071.43      2292655.55      710899.656
     2292538.334      710690.215      2292120.95      710731.109
      2292330.53      710262.576     2291984.091      710371.391
     2292110.543      710182.419     2292028.928       709924.72

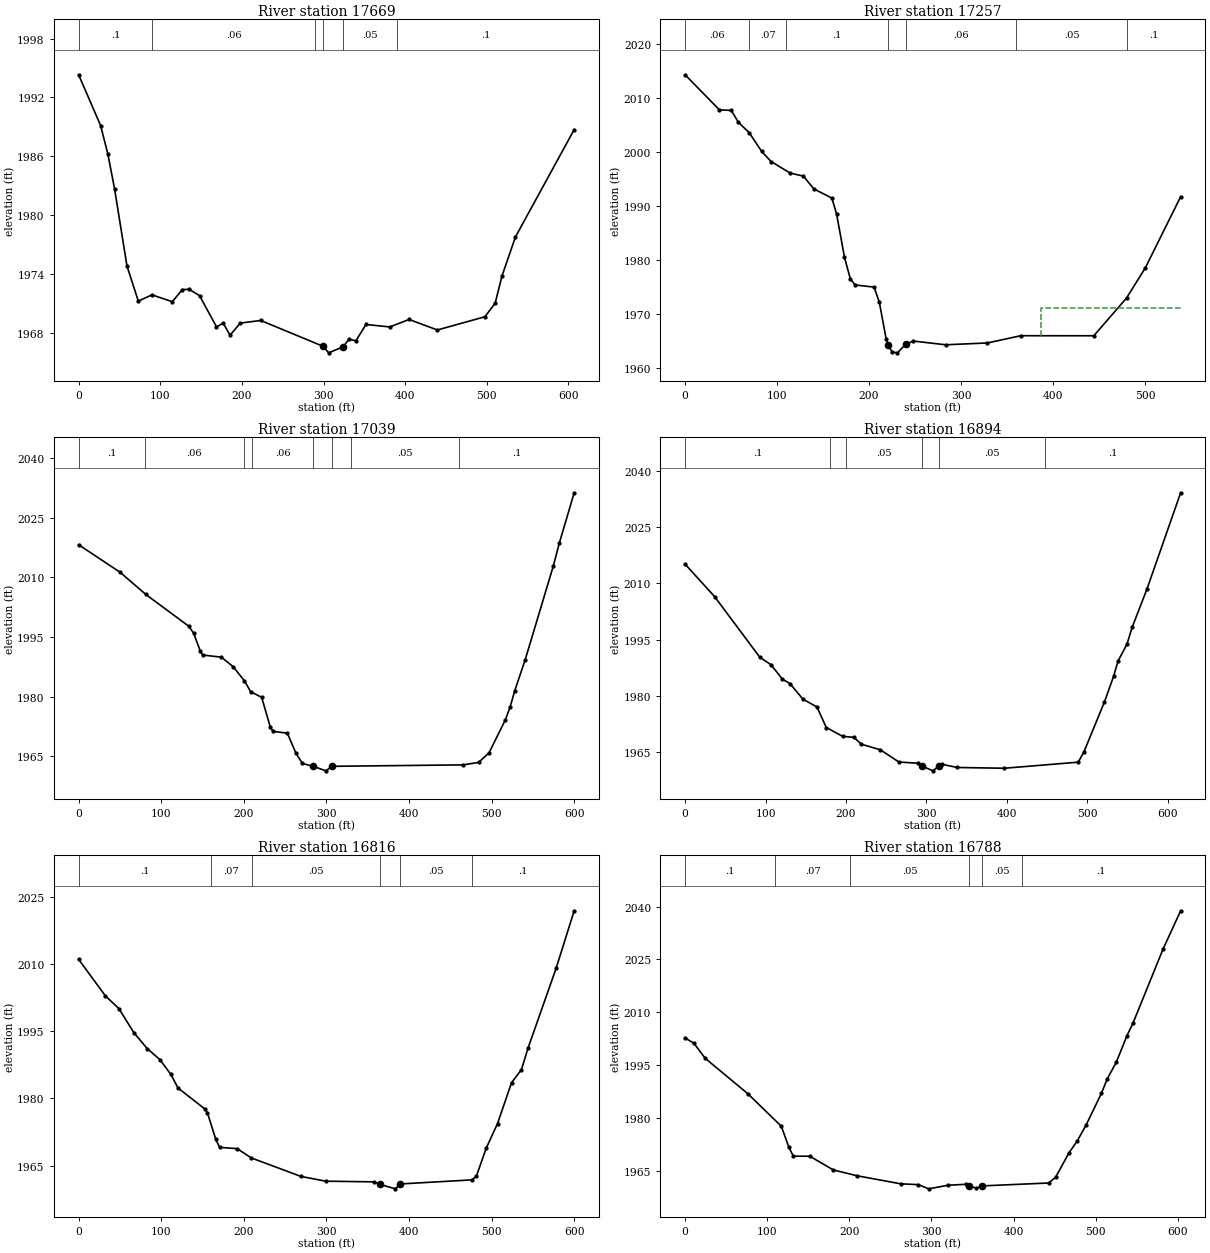
Type RM Length L Ch R = 1 ,17669   ,411.9,411.9,411.9
XS GIS Cut Line= 2
2291519.14926135721743.4489522482291350.87397434721160.118791512
#Sta/Elev= 30
       0 1994.31    26.9 1989.14    35.7 1986.27      44  1982.7    59.2 1974.83
    73.1 1971.24    89.8 1971.88   114.8 1971.18     127 1972.42   135.6 1972.44
   148.1  1971.8   168.9 1968.62   177.2 1968.99   185.5 1967.76     198    1969
     223 1969.27   299.81966.627   306.3 1965.97   324.1 1966.59   331.2 1967.37
   339.6 1967.19   352.1 1968.86   381.2 1968.61   404.9 1969.37   439.5  1968.3
   497.8 1969.65   510.3 1971.03   518.6 1973.79   535.2 1977.79   607.1 1988.72
#Mann= 6, -1 ,  0
       0     0.1       0      90    0.06       0     290    0.05       0
   299.8   0.045       0   324.1    0.05       0     390     0.1       0
Bank Sta=299.8,324.1
XS Rating Curve= 0 ,0
Exp/Cntr(USF)=0,0
Exp/Cntr=0.3,0.1

Type RM Length L Ch R = 1 ,17257   ,218,218,218
XS GIS Cut Line= 2
2291819.19787016721550.6904520412291486.41668584 721126.98544687
#Sta/Elev= 30
       0 2014.32    37.3 2007.83    50.2 2007.72    57.9 2005.53    69.7 2003.61
    83.3 2000.13    93.5 1998.26   114.3 1996.12   128.6 1995.56     140  1993.2
   159.6 1991.49   164.7 1988.56   173.3 1980.54   179.7 1976.51     185 1975.41
   205.5 1975.02   211.2  1972.2   218.6 1965.43   220.6  1964.3   225.1 1963.02
   230.8 1962.85   239.7  1964.4   248.2 1965.03   283.4 1964.34   328.7 1964.68
     365 1966.02   444.4 1966.01     480    1973   500.4 1978.58   538.8 1991.75
#Mann= 7, -1 ,  0
       0    0.06       0      70    0.07       0     110     0.1       0
   220.6   0.045       0   239.7    0.06       0     360    0.05       0
     480     0.1       0
#XS Ineff= 2 , 0
                             387         1971.14
Permanent Ineff=
       F       F
Bank Sta=220.6,239.7
XS Rating Curve= 0 ,0
Exp/Cntr(USF)=0,0
Exp/Cntr=0.3,0.1

Type RM Length L Ch R = 1 ,17039   ,145.1,145.1,145.1
XS GIS Cut Line= 2
2292001.03635239721427.8321659792291618.32621568720965.735908409
#Sta/Elev= 30
       0 2018.23    50.2  2011.3    81.4 2005.72   133.2 1997.76   139.3 1995.97
   147.4 1991.43   150.2 1990.49   172.9 1989.95   187.2 1987.54   200.8 1983.98
   208.3 1981.26   221.6 1979.86     232 1972.44   235.4 1971.28   252.7 1970.86
   263.1  1965.8     271 1963.22   283.9 1962.51   299.5 1961.37   306.5 1962.51
   465.7 1962.87   484.2 1963.49   496.8 1965.86   516.7  1974.2   522.4 1977.39
   528.1 1981.54   540.7 1989.32   574.8 2012.91     582 2018.62     600 2031.29
#Mann= 8, -1 ,  0
       0     0.1       0      80    0.06       0     200     0.1       0
     210    0.06       0   283.9   0.045       0   306.5    0.06       0
     330    0.05       0     460     0.1       0
Bank Sta=283.9,306.5
XS Rating Curve= 0 ,0
Exp/Cntr(USF)=0,0
Exp/Cntr=0.3,0.1

Type RM Length L Ch R = 1 ,16894   ,78.2,78.2,78.2
XS GIS Cut Line= 4
2292069.97726755721336.502564303 2291931.2548954721108.211416424
2291739.00971823720991.3350871272291646.16403608720909.412426405
#Sta/Elev= 30
       0 2015.11    36.7 2006.46    92.8 1990.34   106.9  1988.3   120.9 1984.49
   130.3 1983.32   146.4 1979.18   163.9 1977.07   175.5 1971.61   195.8 1969.25
   209.8    1969   219.1 1967.16   242.6 1965.68   265.8 1962.41   289.5  1962.1
   294.1 1961.36   308.2 1960.07     315 1961.35   319.2 1961.81   338.5 1960.96
   396.8 1960.76   488.6 1962.38   495.7 1965.11   521.2 1978.43   532.5  1985.2
   538.2 1989.37   549.2 1993.81   555.8 1998.39     574 2008.46   615.9 2034.12
#Mann= 6, -1 ,  0
       0     0.1       0     180    0.06       0     200    0.05       0
   294.1   0.045       0     315    0.05       0  447.13     0.1       0
Bank Sta=294.1,315
XS Rating Curve= 0 ,0
Exp/Cntr(USF)=0,0
Exp/Cntr=0.3,0.1

Type RM Length L Ch R = 1 ,16816   ,27.5,27.5,27.5
XS GIS Cut Line= 4
2292097.89946416721299.4141151982291906.40945886721035.103967025
2291812.01297736 721004.087980252291678.50938211720892.160723625
#Sta/Elev= 30
       0 2011.05    32.4  2002.9    48.7 2000.07      67 1994.65      83 1991.13
    98.4 1988.67   111.7 1985.36   120.3 1982.33   152.9 1977.64   155.9 1976.81
   166.1 1970.84   170.7 1969.07   191.9 1968.79   209.1 1966.71   269.2 1962.58
   299.1 1961.52   358.2 1961.37   364.5 1960.83   364.5 1960.82   383.5 1959.81
   389.6  1960.9     476 1961.81   481.6 1962.63   493.4 1968.85   507.2 1974.39
   524.2 1983.53   536.1  1986.4   544.1 1991.22   578.2 2009.09     600  2021.9
#Mann= 6, -1 ,  0
       0     0.1       0     160    0.07       0     210    0.05       0
   364.5   0.045       0   389.6    0.05       0  475.75     0.1       0
Bank Sta=364.5,389.6
XS Rating Curve= 0 ,0
Exp/Cntr(USF)=0,0
Exp/Cntr=0.3,0.1

Type RM Length L Ch R = 1 ,16788   ,119.4,119.4,119.4
XS GIS Cut Line= 6
2292083.18844678721266.4360301292292017.32173018721153.343425619
2291919.82750506721018.4344425272291891.69844148721002.125881956
2291797.30195998 720971.109895182291663.79836473720859.182638556
#Sta/Elev= 30
       0 2002.65    10.7 2001.17    24.6 1996.85    76.3 1986.84   117.2 1977.57
   126.4 1971.58   131.8 1969.09   151.9 1969.06   180.4 1965.18   209.2 1963.52
   262.6 1961.23   284.1 1960.99   296.7  1959.8     320 1960.82     342 1961.09
345.65341960.639   354.6 1959.96361.95331960.638   442.7 1961.46   451.2 1963.11
   467.2 1969.93   477.7 1973.49   488.2 1977.89   506.9 1986.92   514.2 1991.11
   525.1  1995.8     538 2003.27   545.5 2006.94     582 2027.92   603.4 2038.79
#Mann= 6, -1 ,  0
       0     0.1       0     110    0.07       0  200.88    0.05       0
345.6534   0.045       0361.9533    0.05       0  409.84     0.1       0
Bank Sta=345.6534,361.9533
XS Rating Curve= 0 ,0
Exp/Cntr(USF)=0,0
Exp/Cntr=0.3,0.1

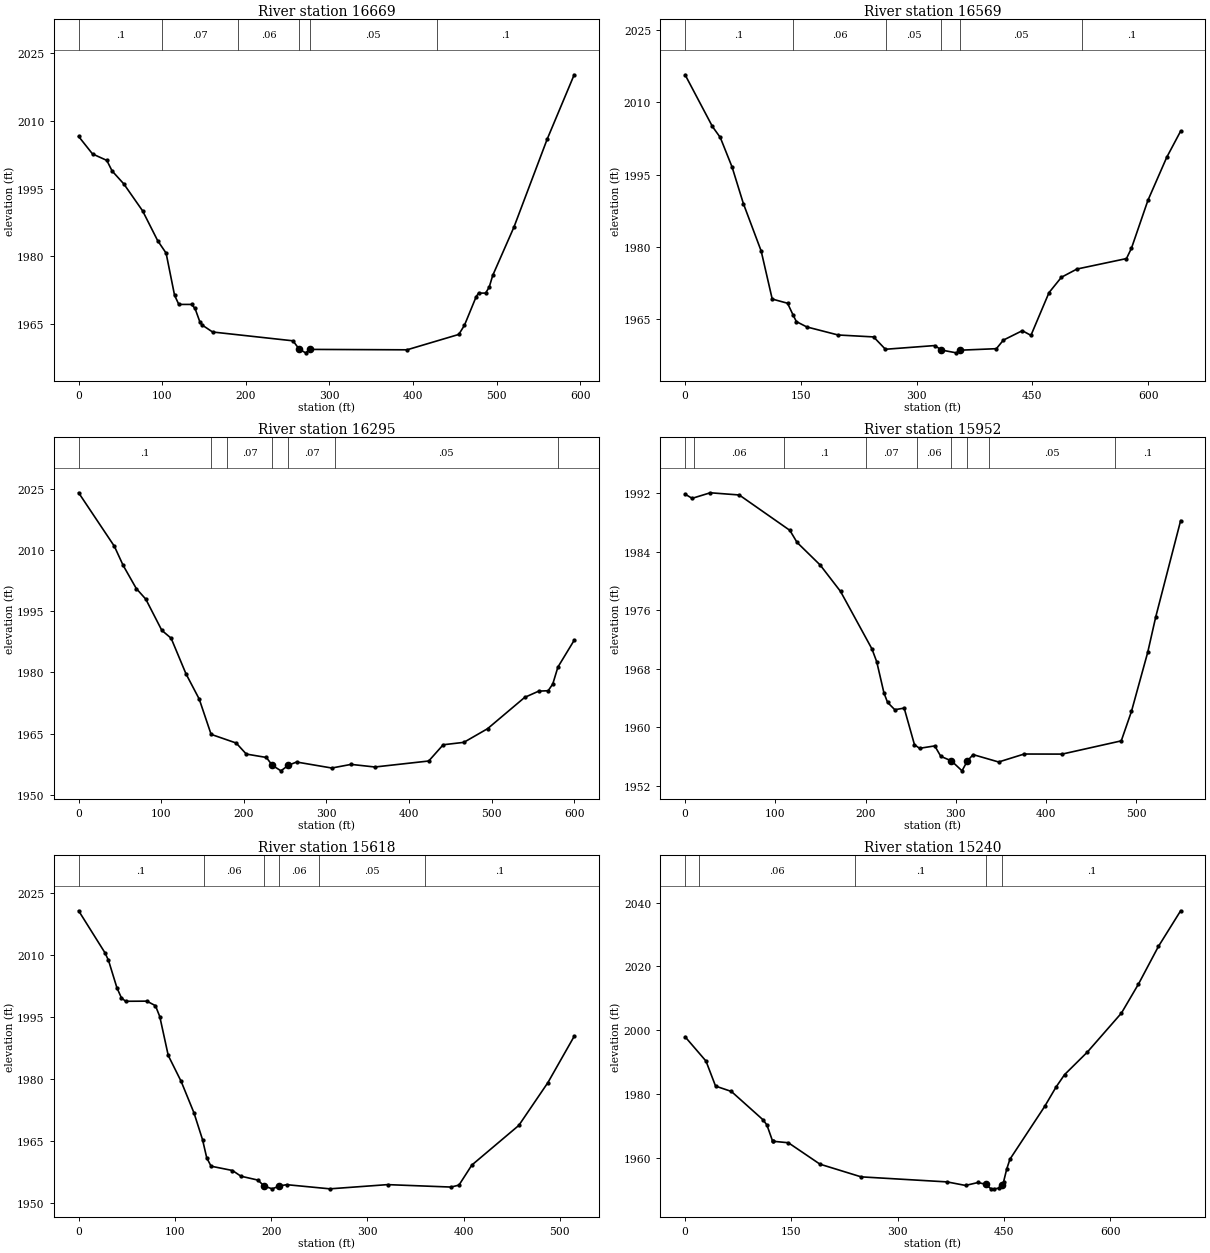
Type RM Length L Ch R = 1 ,16669   ,100.1,100.1,100.1
XS GIS Cut Line= 3
2292136.60769827721223.9954435782291881.00899682 720893.02789426
2291716.07137323720836.228182826
#Sta/Elev= 30
       0 2006.55    16.6 2002.68    33.7 2001.25      40 1998.92    54.1 1996.03
    76.5 1990.09    94.5  1983.5   104.6 1980.74   114.7 1971.43   119.8 1969.39
     135 1969.39   139.2  1968.5   144.9 1965.57   147.8 1964.82   160.2 1963.29
   256.3 1961.34  263.84 1959.49   271.4 1958.68   276.5 1959.44   392.7 1959.35
   454.6 1962.75   461.4 1964.78   475.4  1971.1   478.3 1971.89   486.7  1971.9
     491 1973.22   495.2 1975.81   520.6  1986.5   560.3 2005.94   592.6 2020.19
#Mann= 6, -1 ,  0
       0     0.1       0     100    0.07       0     190    0.06       0
  263.84   0.045       0   276.5    0.05       0  428.17     0.1       0
Bank Sta=263.84,276.5
XS Rating Curve= 0 ,0
Exp/Cntr(USF)=0,0
Exp/Cntr=0.3,0.1

Type RM Length L Ch R = 1 ,16569   ,273.4,273.4,273.4
XS GIS Cut Line= 3
2292210.95316158721180.9476115182291922.85102593720816.025979555
2291746.19044049720801.480072609
#Sta/Elev= 30
       0 2015.69    35.4 2004.97    45.6 2002.69    60.9 1996.56    75.5    1989
    98.6 1979.15   112.9  1969.2   132.8 1968.33     140 1965.87   144.2 1964.53
   157.7 1963.42   198.3 1961.75   244.3 1961.35   259.6 1958.79   323.6 1959.56
   332.2 1958.63   351.4 1958.05   356.4  1958.6   403.4 1958.91   412.5 1960.69
     437 1962.64   448.2 1961.67   471.6 1970.53   487.7 1973.72   507.8 1975.42
     572 1977.59   578.5 1979.75   599.8 1989.66   624.2 1998.59   642.2 2004.01
#Mann= 6, -1 ,  0
       0     0.1       0     140    0.06       0     260    0.05       0
   332.2   0.045       0   356.4    0.05       0  514.94     0.1       0
Bank Sta=332.2,356.4
XS Rating Curve= 0 ,0
Exp/Cntr(USF)=0,0
Exp/Cntr=0.3,0.1

Type RM Length L Ch R = 1 ,16295   ,342.6,342.6,342.6
XS GIS Cut Line= 2
2292373.60840012721013.8050055692291979.22757009720561.628313434
#Sta/Elev= 30
       0 2024.01    43.3 2010.89    53.9 2006.22    69.8 2000.55    81.3 1997.95
   100.7 1990.31     112 1988.37     130 1979.64     146 1973.47   160.4 1964.82
   190.8 1962.69     203 1959.99   227.3 1959.16   234.51957.226     245 1955.88
   253.8 1957.23   263.9 1958.04   306.5 1956.57   329.9 1957.46   358.7 1956.82
   423.9 1958.29   441.4 1962.27   466.4 1962.86   495.1  1966.2   540.1 1973.88
   557.1 1975.41   568.5 1975.51   574.1 1977.16   580.3  1981.3     600 1987.87
#Mann= 7, -1 ,  0
       0     0.1       0     160    0.06       0     180    0.07       0
   234.5   0.045       0   253.8    0.07       0     310    0.05       0
     580     0.1       0
Bank Sta=234.5,253.8
XS Rating Curve= 0 ,0
Exp/Cntr(USF)=0,0
Exp/Cntr=0.3,0.1

Type RM Length L Ch R = 1 ,15952   ,334.4,334.4,334.4
XS GIS Cut Line= 3
 2292363.6765866720880.9678276732292381.10708302720645.089196353
2292151.97905448720432.327455559
#Sta/Elev= 30
       0 1991.86     7.8 1991.29    27.9 1992.05      60 1991.75   116.1 1986.91
   124.1 1985.26   149.7 1982.17   172.3 1978.55   207.1 1970.69   212.4 1968.93
   220.4 1964.67   224.4 1963.38   232.4 1962.38   242.8  1962.6   254.2  1957.6
   259.8  1957.1   276.7 1957.43   283.4    1956   295.2 1955.38   306.9 1954.02
   312.8 1955.37   319.2 1956.24   347.5 1955.23   375.8 1956.32   417.9 1956.31
   483.4 1958.12   494.7 1962.15   512.7 1970.22   521.6 1975.07   549.2 1988.24
#Mann= 9, -1 ,  0
       0     0.1       0      10    0.06       0     110     0.1       0
     200    0.07       0  256.52    0.06       0   295.2   0.045       0
   312.8    0.06       0  336.52    0.05       0  476.52     0.1       0
Bank Sta=295.2,312.8
XS Rating Curve= 0 ,0
Exp/Cntr(USF)=0,0
Exp/Cntr=0.3,0.1

Type RM Length L Ch R = 1 ,15618   ,378,378,378
XS GIS Cut Line= 2
2292692.06655034720537.7990877472292228.35506399720314.126488451
#Sta/Elev= 30
       0 2020.74    27.3 2010.59      31 2008.75    39.8 2002.08    44.3 1999.73
    48.7 1998.83    70.9 1998.86    79.8 1997.76    84.3 1995.12    93.1 1985.71
   106.5 1979.43   119.8 1971.83   128.7 1965.34   133.1 1960.91   137.6  1958.9
   159.8 1957.86   168.6 1956.48   186.4 1955.53   192.61954.101   201.1 1953.42
   208.6 1954.11   216.1 1954.43     261 1953.42   320.9 1954.44   386.9 1953.85
   395.1 1954.32   408.5 1959.18   457.3 1968.78   487.5 1979.14   514.8 1990.34
#Mann= 6, -1 ,  0
       0     0.1       0     130    0.06       0   192.6   0.045       0
   208.6    0.06       0     250    0.05       0     360     0.1       0
Bank Sta=192.6,208.6
XS Rating Curve= 0 ,0
Exp/Cntr(USF)=0,0
Exp/Cntr=0.3,0.1

Type RM Length L Ch R = 1 ,15240   ,235.2,235.2,235.2
XS GIS Cut Line= 3
  2292778.614105720345.6240493972292361.19590131720137.523588389
2292128.94031291720158.077180283
#Sta/Elev= 30
       0 1997.99    29.5 1990.39      43 1982.56    65.3 1980.89     110 1972.02
   115.5 1970.39   123.4 1965.42   124.4 1965.29   145.8 1964.83   190.4 1958.13
   248.5 1954.16   369.9 1952.58   395.9 1951.47   413.7  1952.4     4251951.771
   431.6 1950.44   436.3 1950.41   443.6 1950.63   447.81951.763   449.7 1952.67
   454.1 1956.63   458.6 1959.68   507.6 1976.18   523.7 1982.26   535.7 1986.14
   567.8 1993.18     616  2005.4   640.1  2014.5   668.2 2026.25   699.6 2037.42
#Mann= 5, -1 ,  0
       0     0.1       0      20    0.06       0     240     0.1       0
     425   0.045       0   447.8     0.1       0
Bank Sta=425,447.8
XS Rating Curve= 0 ,0
Exp/Cntr(USF)=0,0
Exp/Cntr=0.3,0.1

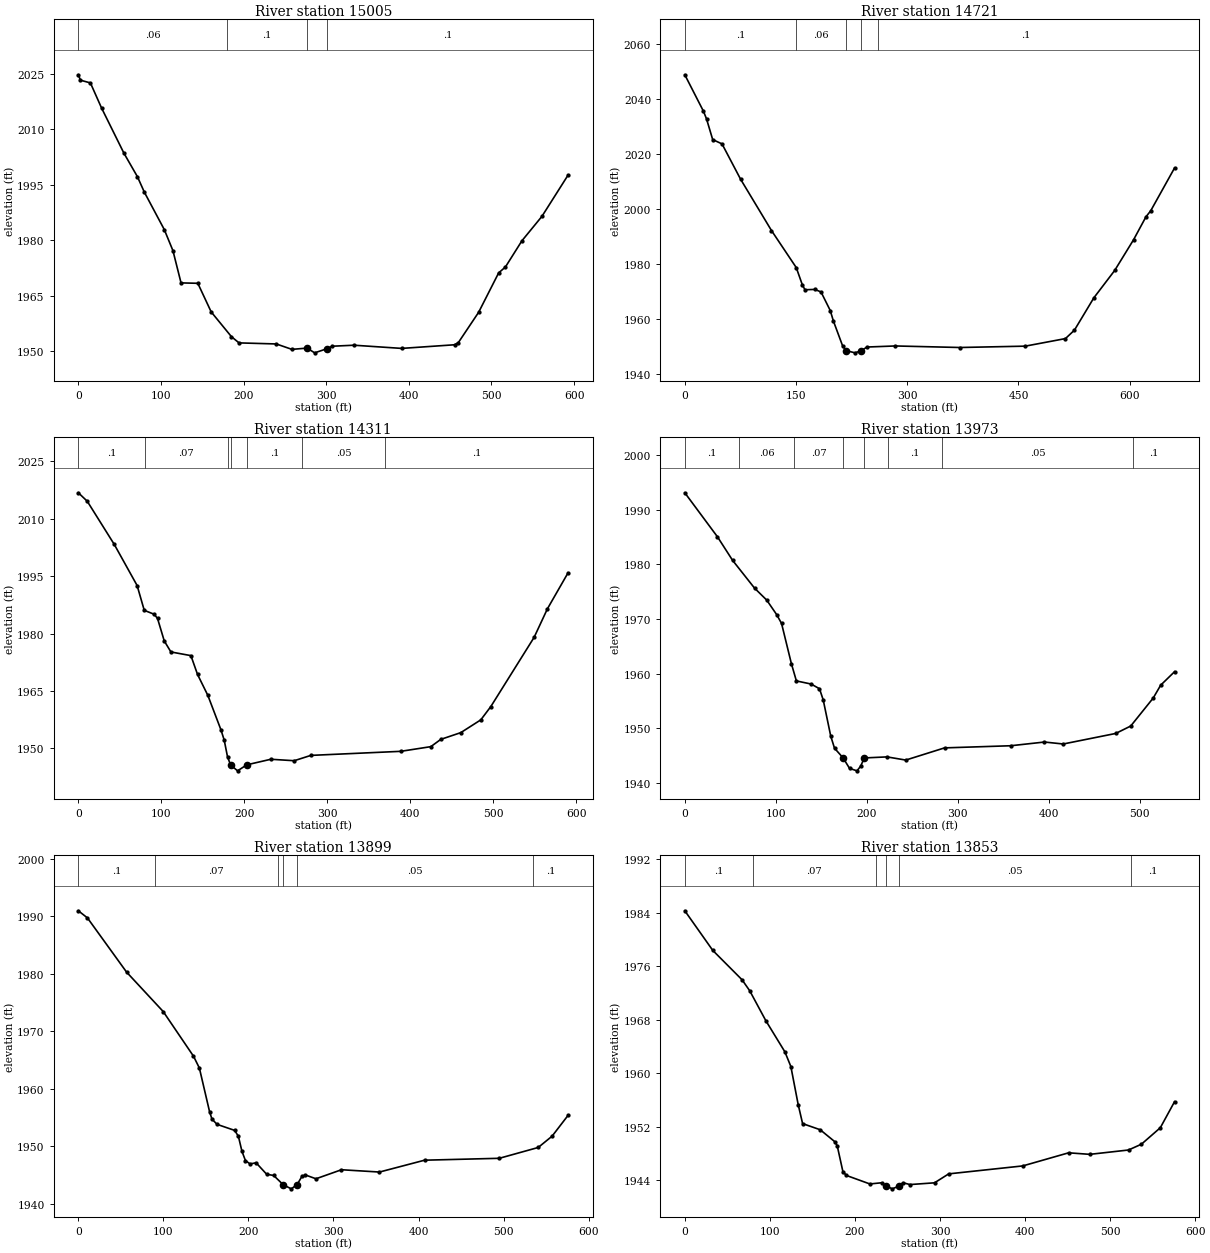
Type RM Length L Ch R = 1 ,15005   ,283.5,283.5,283.5
XS GIS Cut Line= 4
2292834.58876762720091.2781213272292653.26661189720059.601359181
2292409.68323401719924.1558934542292280.79158114 719907.77136131
#Sta/Elev= 30
       0 2024.72     2.5 2023.26    14.6 2022.52    28.1 2015.74    55.2 2003.51
    71.5 1997.17    79.9 1992.98     104 1982.88   114.5 1977.17   124.3 1968.46
   144.6 1968.35   160.8 1960.61   185.3 1953.92   194.5 1952.24   239.6 1951.95
   258.5 1950.49   276.9 1950.83     286 1949.55   301.4  1950.7   307.2 1951.34
   333.7 1951.61   391.3 1950.75   455.3 1951.73   459.9 1952.31   484.5 1960.52
   508.7 1971.16   516.9 1972.76   536.9 1979.85   561.1 1986.45   592.7 1997.59
#Mann= 4, -1 ,  0
       0    0.06       0     180     0.1       0   276.9   0.045       0
   301.4     0.1       0
Bank Sta=276.9,301.4
XS Rating Curve= 0 ,0
Exp/Cntr(USF)=0,0
Exp/Cntr=0.3,0.1

Type RM Length L Ch R = 1 ,14721   ,410.6,410.6,410.6
XS GIS Cut Line= 2
2292908.24331031719970.7388336152292275.21356424719782.109579807
#Sta/Elev= 30
       0 2048.85    25.1 2035.63    29.3 2032.82    37.6 2025.31    50.2 2023.73
    75.2 2010.92   116.9 1992.25   150.3  1978.8   158.7 1972.39   162.1 1970.74
   175.4 1970.85   183.7 1969.94   196.2 1963.17   200.4 1959.39   212.9  1950.3
   217.8  1948.6   229.6 1947.81     238 1948.59   245.7 1949.92   283.9 1950.31
   371.1 1949.75   459.2 1950.24   513.4 1952.99   525.5 1956.05   551.7  1967.8
   579.8 1977.74   605.3 1988.92     622 1997.25   628.4 1999.43   660.5 2014.96
#Mann= 5, -1 ,  0
       0     0.1       0     150    0.06       0   217.8   0.045       0
     238    0.06       0     260     0.1       0
Bank Sta=217.8,238
XS Rating Curve= 0 ,0
Exp/Cntr(USF)=0,0
Exp/Cntr=0.3,0.1

Type RM Length L Ch R = 1 ,14311   ,338.1,338.1,338.1
XS GIS Cut Line= 2
2292935.27555738719550.531422869 2292347.3848013719501.516775108
#Sta/Elev= 30
       0 2016.72    10.7 2014.52    43.3 2003.24    70.8 1992.52    79.4 1986.05
    91.4 1985.02    95.4 1983.92   103.5 1978.06   111.5 1975.19   135.6 1974.23
   143.6 1969.31     156 1963.86   171.7 1954.92   175.7  1952.2   179.7 1947.83
   183.41945.712   191.8 1944.17   202.91945.738   231.9 1947.19     260 1946.81
   280.1  1948.2   388.4 1949.26   424.6 1950.48   436.6 1952.38   460.7 1954.14
   484.8 1957.47   496.9 1960.95     549 1978.99   565.1 1986.47   589.9 1995.83
#Mann= 7, -1 ,  0
       0     0.1       0      80    0.07       0     180     0.1       0
   183.4   0.045       0   202.9     0.1       0     270    0.05       0
     370     0.1       0
Bank Sta=183.4,202.9
XS Rating Curve= 0 ,0
Exp/Cntr(USF)=0,0
Exp/Cntr=0.3,0.1

Type RM Length L Ch R = 1 ,13973   ,73.6,73.6,73.6
XS GIS Cut Line= 3
2292906.64676755719284.8688364032292801.17513536  719188.4895863
2292417.47661137719283.050359986
#Sta/Elev= 30
       0 1993.09    35.9 1985.03    52.5 1980.73    76.6 1975.65      90 1973.46
   100.9 1970.81   106.3 1969.19   117.1 1961.84   122.6 1958.67   138.8  1958.1
     148 1957.24   152.1 1955.19   160.4 1948.54   164.5 1946.36     174 1944.58
     181 1942.67   189.2 1942.22   193.3 1943.09   197.2 1944.58   222.2 1944.77
   242.8 1944.19   285.4 1946.42   358.1 1946.81   395.2 1947.49   415.8 1947.13
   473.5 1949.06     490 1950.42   514.7 1955.54   522.9 1957.89   538.1 1960.35
#Mann= 8, -1 ,  0
       0     0.1       0      60    0.06       0     120    0.07       0
     174   0.045       0   197.2    0.05       0  222.87     0.1       0
  282.87    0.05       0  492.87     0.1       0
Bank Sta=174,197.2
XS Rating Curve= 0 ,0
Exp/Cntr(USF)=0,0
Exp/Cntr=0.3,0.1

Type RM Length L Ch R = 1 ,13899   ,45.6,45.6,45.6
XS GIS Cut Line= 3
2292910.56427718719261.8964126242292803.77754814719111.445807142
2292426.28843666719214.383897876
#Sta/Elev= 30
       0 1990.93    10.7 1989.69    56.7 1980.27    99.8 1973.41   135.4 1965.65
   142.3  1963.6   154.3    1956   157.1 1954.72   163.1  1953.8   183.8 1952.75
   188.2 1951.72   192.4  1949.1   196.5  1947.5   201.9 1946.92     209 1947.12
   221.4 1945.13   229.7 1944.91     241 1943.29   250.4 1942.59   257.3 1943.34
   262.9 1944.76     267    1945   279.4 1944.34   309.4 1945.91   354.1 1945.51
   407.1 1947.57     495  1947.9   540.7 1949.78     557 1951.74   575.8 1955.36
#Mann= 6, -1 ,  0
       0     0.1       0      90    0.07       0   234.5    0.05       0
     241   0.045       0   257.3    0.05       0   534.5     0.1       0
Bank Sta=241,257.3
XS Rating Curve= 0 ,0
Exp/Cntr(USF)=0,0
Exp/Cntr=0.3,0.1

Type RM Length L Ch R = 1 ,13853   ,126,126,126
XS GIS Cut Line= 3
2292904.32491156719218.9207482572292797.53818253719068.470142775
2292420.04907105719171.408233509
#Sta/Elev= 30
       0 1984.32    32.9 1978.39    67.3    1974    76.3 1972.36    95.3 1967.87
   117.7 1963.21   124.7 1961.02   133.3 1955.33   138.5 1952.48   159.2 1951.56
   176.4 1949.77   179.2 1949.17   185.9 1945.29   190.1 1944.72   217.6 1943.45
   231.5 1943.63   236.7 1943.16     244 1942.72   252.2 1943.16   256.4 1943.64
   264.7 1943.36   293.6 1943.62   310.3 1944.96   397.4 1946.15   451.3 1948.11
   476.2 1947.88   521.7 1948.53   536.9  1949.4   559.1 1951.86   575.8 1955.75
#Mann= 6, -1 ,  0
       0     0.1       0      80    0.07       0   224.5    0.05       0
   236.7   0.045       0   252.2    0.05       0   524.5     0.1       0
Bank Sta=236.7,252.2
XS Rating Curve= 0 ,0
Exp/Cntr(USF)=0,0
Exp/Cntr=0.3,0.1

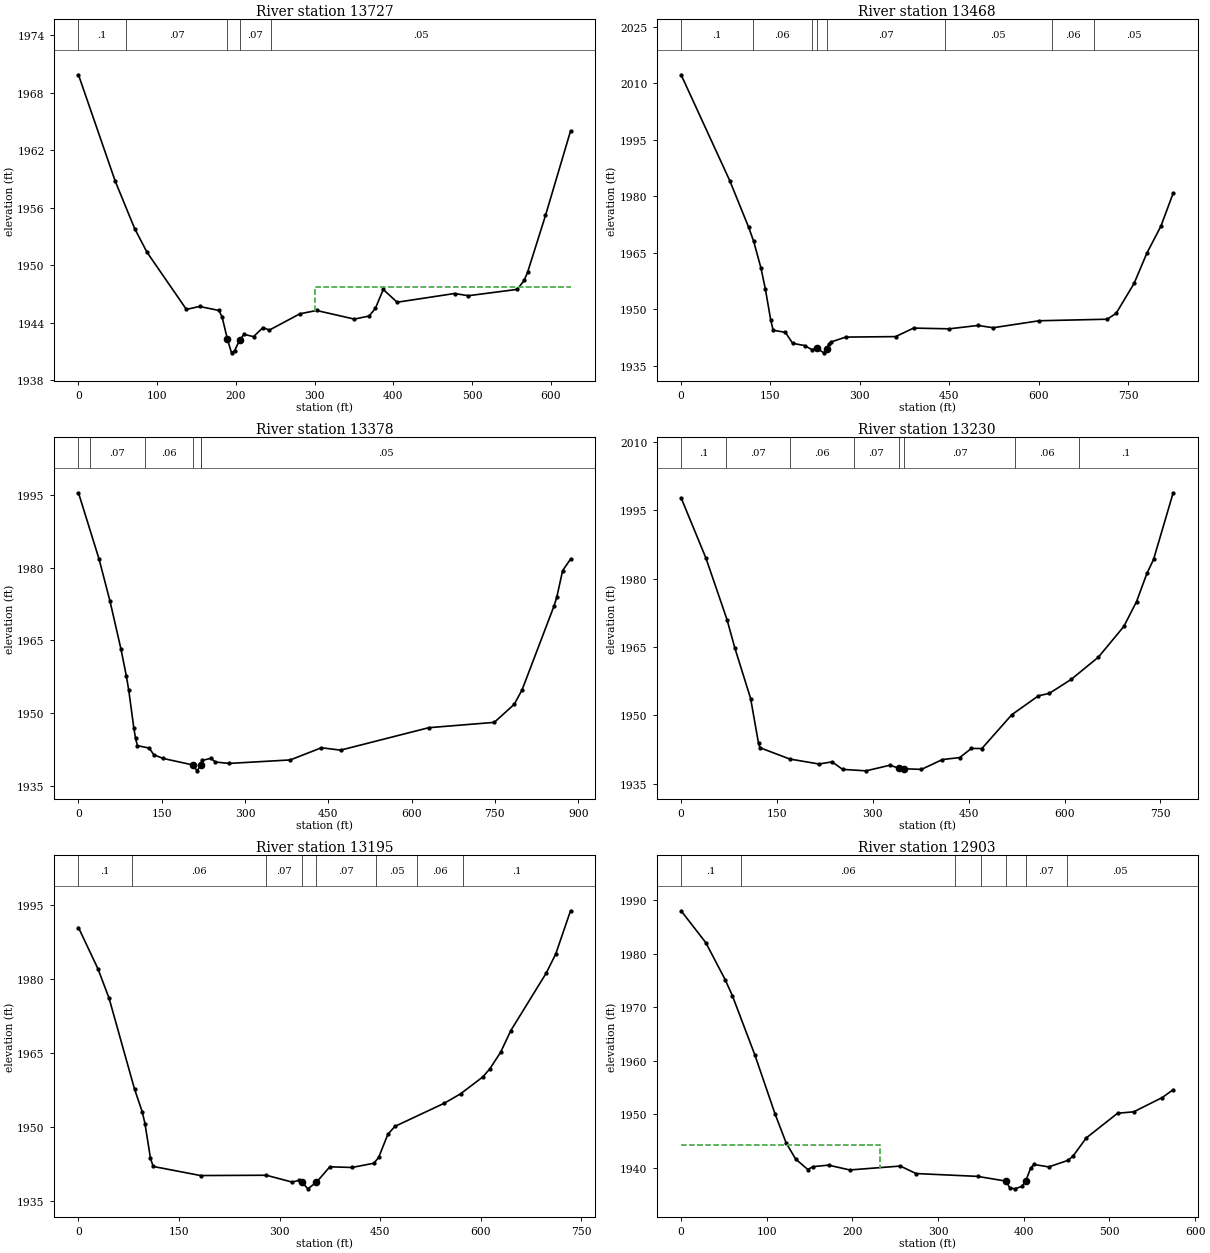
Type RM Length L Ch R = 1 ,13727   ,259.8,259.8,259.8
XS GIS Cut Line= 4
2292875.03569865719142.7297407322292838.03923325 718982.41172396
2292624.28187755 718982.411723962292398.19236672 719081.06896505
#Sta/Elev= 30
       0 1969.89    46.7 1958.79    71.4 1953.84    87.1 1951.37   137.1 1945.41
   153.8 1945.72   178.4  1945.3   182.4 1944.64   189.2  1942.3   194.4 1940.88
   198.4 1941.11     2051942.259   210.4 1942.81   222.4 1942.57   234.4 1943.52
   242.4 1943.25   281.2 1944.95   302.4  1945.3   350.4  1944.4   369.2 1944.72
   377.2 1945.53   387.1 1947.49   404.8 1946.16   477.7 1947.07   495.2 1946.84
   557.3  1947.5   566.1 1948.44   570.4 1949.27   593.2 1955.21     625 1964.02
#Mann= 5, -1 ,  0
       0     0.1       0      60    0.07       0   189.2   0.045       0
     205    0.07       0  244.53    0.05       0
#XS Ineff= 2 , 0
                          300.73         1947.73
Permanent Ineff=
       F       F
Bank Sta=189.2,205
XS Rating Curve= 0 ,0
Exp/Cntr(USF)=0,0
Exp/Cntr=0.3,0.1

Type RM Length L Ch R = 1 ,13468   ,89.6,89.6,89.6
XS GIS Cut Line= 4
2293070.54652786718781.004822846 2292905.8660865718741.934698804
2292774.32309838 718721.381106912292355.64841319719035.737567268
#Sta/Elev= 30
       0 2012.29    81.6 1984.19   113.4 1971.78   121.7  1968.1     134    1961
   141.4  1955.4   150.4 1947.18   154.5 1944.45     175 1943.88   187.2 1940.97
   207.4 1940.37   219.5 1939.28     228 1939.61   239.8 1938.44   244.9 1939.58
   247.9 1940.77   251.9 1941.34   276.2 1942.62   360.1 1942.75   390.1 1945.01
   450.1 1944.82   498.1 1945.71   523.8 1945.11   600.9 1946.96   715.2 1947.37
   730.2 1948.94   760.3 1956.87   781.7  1964.9   805.3 1972.08   825.9 1980.85
#Mann= 8, -1 ,  0
       0     0.1       0     120    0.06       0  219.25    0.07       0
     228   0.045       0   244.9    0.07       0  442.39    0.05       0
  622.39    0.06       0  692.39    0.05       0
Bank Sta=228,244.9
XS Rating Curve= 0 ,0
Exp/Cntr(USF)=0,0
Exp/Cntr=0.3,0.1

Type RM Length L Ch R = 1 ,13378   ,148.3,148.3,148.3
XS GIS Cut Line= 3
 2293072.1281215718697.5009536982292770.26103627718624.761897016
2292321.09736126718984.820227591
#Sta/Elev= 30
       0 1995.43      37 1981.79    56.6 1973.16    76.5 1963.22    86.4 1957.54
    90.5 1954.76    99.7 1946.94   102.8 1944.75   106.3 1943.27   127.5 1942.76
   135.7 1941.38   152.7 1940.62   205.7 1939.29   213.9 1938.07   219.8 1939.19
   222.4 1940.21   238.6 1940.65   246.8 1939.89   271.5  1939.6   381.5 1940.32
   437.5 1942.83   472.1 1942.34   630.9 1946.97   748.9 1948.07   784.8 1951.79
   798.9 1954.76   856.6 1972.11   861.5 1973.92     872 1979.38   886.2 1981.75
#Mann= 6, -1 ,  0
       0     0.1       0      20    0.07       0     120    0.06       0
   205.7   0.045       0   219.8    0.06       0     220    0.05       0
Bank Sta=205.7,219.8
XS Rating Curve= 0 ,0
Exp/Cntr(USF)=0,0
Exp/Cntr=0.3,0.1

Type RM Length L Ch R = 1 ,13230   ,34.7,34.7,34.7
XS GIS Cut Line= 3
2293122.01796388718656.100289139 2292653.0569062718544.620216624
2292471.38242935718321.361842438
#Sta/Elev= 30
       0 1997.69    38.9 1984.45    71.8    1971    84.1 1964.76   108.8 1953.67
   121.1 1943.89   123.5  1942.9     170 1940.43   215.7 1939.34   236.2  1939.8
   252.7 1938.16   289.4 1937.84   326.7 1939.07   341.2  1938.4   349.1 1938.29
   376.1 1938.16   408.9 1940.32   435.8 1940.74   454.2 1942.75   470.6 1942.73
   517.4 1950.14     559 1954.28   576.1 1954.82   610.2 1957.87   652.9 1962.76
   692.7 1969.49   712.6 1974.94   728.8 1981.11   739.2 1984.17   769.9 1998.79
#Mann= 8, -1 ,  0
       0     0.1       0      70    0.07       0     170    0.06       0
     270    0.07       0   341.2   0.045       0   349.1    0.07       0
  522.03    0.06       0  622.03     0.1       0
Bank Sta=341.2,349.1
XS Rating Curve= 0 ,0
Exp/Cntr(USF)=0,0
Exp/Cntr=0.3,0.1

Type RM Length L Ch R = 1 ,13195   ,291.7,291.7,291.7
XS GIS Cut Line= 3
2293128.59080864  718623.93194692292706.49624513718522.011265541
2292512.89638033718293.304218576
#Sta/Elev= 30
       0 1990.34    29.2 1981.95    45.7 1976.01    83.6 1957.66    95.1 1953.06
    99.2 1950.66   107.4 1943.64   111.5 1941.99   182.1 1940.15   280.2 1940.21
   318.5 1938.83   329.6 1939.19   333.7 1938.79     342 1937.46   354.9 1938.78
   374.9 1941.92   407.8 1941.78   440.6 1942.64   447.8 1943.83   461.5 1948.51
     472  1950.1   545.4 1954.77   569.9 1956.69     603  1960.1   613.5 1961.73
   629.5 1965.07   644.9  1969.5   697.6 1981.11   711.8 1984.97   733.9 1993.73
#Mann= 8, -1 ,  0
       0     0.1       0      80    0.06       0     280    0.07       0
   333.7   0.045       0   354.9    0.07       0  444.23    0.05       0
  504.23    0.06       0  574.23     0.1       0
Bank Sta=333.7,354.9
XS Rating Curve= 0 ,0
Exp/Cntr(USF)=0,0
Exp/Cntr=0.3,0.1

Type RM Length L Ch R = 1 ,12903   ,155.6,155.6,155.6
XS GIS Cut Line= 2
2293205.93357924718539.9777746612292766.47173239718170.066367855
#Sta/Elev= 30
       0 1988.05    28.8  1982.1    51.5 1975.15    59.8  1972.2      86 1961.14
   109.9 1949.97   122.6 1944.66   133.8 1941.62     148 1939.68   153.9 1940.22
   172.1  1940.5   196.9  1939.6   255.9 1940.33   274.2 1938.93     346  1938.4
   379.4 1937.51   383.6 1936.27   389.2 1936.07   397.8 1936.52   402.31937.507
   408.1 1939.99     412 1940.62   429.1 1940.17   451.6 1941.39   457.5 1942.19
   472.9 1945.58   509.5  1950.2   528.4 1950.47   561.7 1953.14   574.4 1954.61
#Mann= 7, -1 ,  0
       0     0.1       0      70    0.06       0     320    0.05       0
     350    0.07       0   379.4   0.045       0   402.3    0.07       0
     450    0.05       0
#XS Ineff= 2 , 0
          232.33 1944.34
Permanent Ineff=
       F       F
Bank Sta=379.4,402.3
XS Rating Curve= 0 ,0
Exp/Cntr(USF)=0,0
Exp/Cntr=0.3,0.1

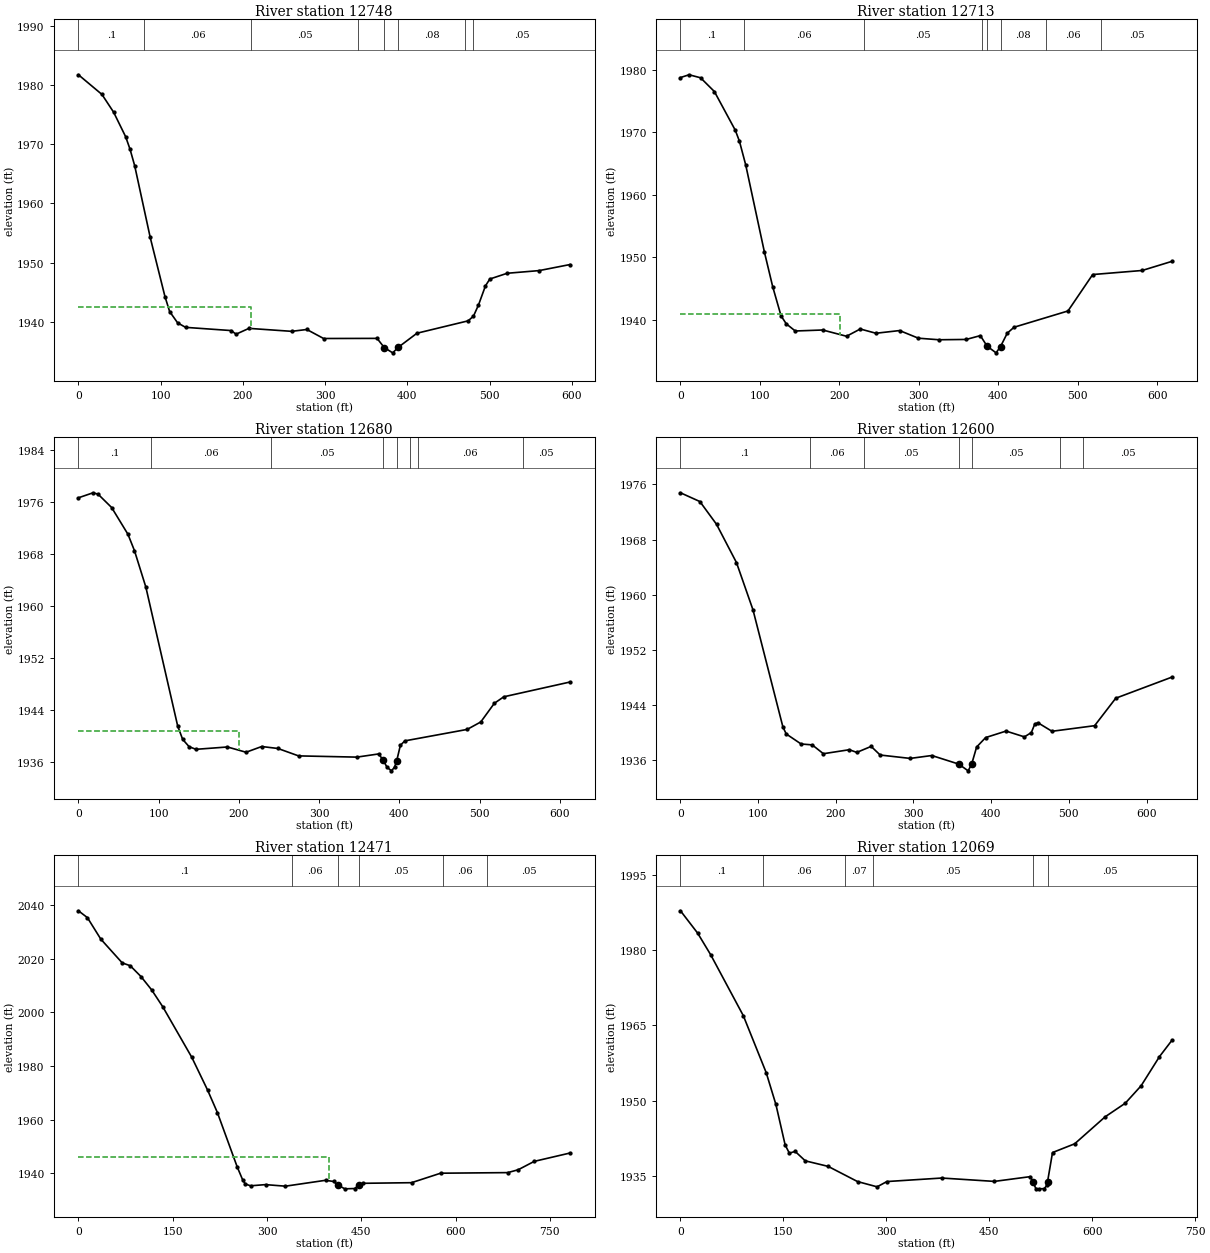
Type RM Length L Ch R = 1 ,12748   ,34.4,34.4,34.4
XS GIS Cut Line= 2
2293273.05181444718476.6923930322292883.74599739718023.265617872
#Sta/Elev= 30
       0 1981.72    28.6  1978.4    42.8  1975.4    57.4 1971.27    62.8 1969.13
    68.4 1966.37    87.3 1954.26   105.2 1944.29   110.9 1941.76   120.6 1939.85
   130.3 1939.09   185.6 1938.55   191.7 1937.94   207.3 1938.92   259.2 1938.42
   277.7 1938.73   298.1 1937.21   363.1 1937.23   371.9 1935.67   382.1 1934.79
   388.9 1935.73   411.6  1938.1   473.8 1940.19   480.3 1940.98   486.4 1942.86
   494.9  1946.1   500.2 1947.25   521.3 1948.22   560.1 1948.67   597.6 1949.69
#Mann= 8, -1 ,  0
       0     0.1       0      80    0.06       0     210    0.05       0
     340    0.08       0   371.9   0.045       0   388.9    0.08       0
     470    0.06       0     480    0.05       0
#XS Ineff= 2 , 0
          209.61 1942.45
Permanent Ineff=
       F       F
Bank Sta=371.9,388.9
XS Rating Curve= 0 ,0
Exp/Cntr(USF)=0,0
Exp/Cntr=0.3,0.1

Type RM Length L Ch R = 1 ,12713   ,33.6,33.6,33.6
XS GIS Cut Line= 5
2293303.20393165718461.8071706152293160.07679302718292.726310854
2293114.65778103718260.2841594332293073.43716511718189.293098676
2292893.28780663 718003.03698228
#Sta/Elev= 30
       0 1978.74    10.9 1979.18    25.3  1978.7    42.7  1976.5      69 1970.32
    74.2 1968.57    82.1 1964.79   105.6 1950.88   116.1 1945.31   126.6 1940.66
   133.2 1939.38   144.5 1938.24     179  1938.4     209  1937.4   226.3 1938.56
     246 1937.88   275.8 1938.31   299.4 1937.09   325.3 1936.84   359.6 1936.89
   377.4  1937.5   385.9 1935.82   397.2 1934.75   402.8 1935.75   411.3 1937.89
   419.8 1938.84   487.7 1941.44   518.8 1947.26   581.1 1947.91   618.6 1949.37
#Mann= 8, -1 ,  0
       0     0.1       0      80    0.06       0  231.53    0.05       0
  379.43    0.08       0   385.9   0.045       0   402.8    0.08       0
  459.43    0.06       0  529.43    0.05       0
#XS Ineff= 2 , 0
          201.41 1940.97
Permanent Ineff=
       F       F
Bank Sta=385.9,402.8
XS Rating Curve= 0 ,0
Exp/Cntr(USF)=0,0
Exp/Cntr=0.3,0.1

Type RM Length L Ch R = 1 ,12680   ,79.7,79.7,79.7
XS GIS Cut Line= 4
2293311.98239615718447.6852929372293137.93979558718241.582213319
2293099.00921388718167.537773605 2292918.8598554717981.281657209
#Sta/Elev= 30
       0 1976.58    18.3 1977.35    24.5 1977.13    41.4 1975.08    61.7 1970.97
    69.8 1968.46      84 1962.85   123.7 1941.47   129.9 1939.42   137.9  1938.3
   146.4 1937.89   185.7 1938.25   208.9 1937.44   228.4 1938.32   248.6 1938.02
   274.3 1936.88     347 1936.69   374.1 1937.18   379.7 1936.24   384.5 1935.14
   390.1 1934.58   393.9 1935.14   396.7 1936.17   401.2 1938.51   406.8 1939.19
   484.4 1940.95   501.4  1942.1   518.3 1944.97   530.1 1945.97   612.5 1948.24
#Mann= 8, -1 ,  0
       0     0.1       0      90    0.06       0     240    0.05       0
   379.7   0.045       0   396.7    0.05       0  413.41    0.08       0
  423.41    0.06       0  553.41    0.05       0
#XS Ineff= 2 , 0
          200.23 1940.75
Permanent Ineff=
       F       F
Bank Sta=379.7,396.7
XS Rating Curve= 0 ,0
Exp/Cntr(USF)=0,0
Exp/Cntr=0.3,0.1

Type RM Length L Ch R = 1 ,12600   ,128.7,128.7,128.7
XS GIS Cut Line= 4
2293319.61584354718428.6016744542293271.52512497718301.123102987
 2293122.6729008718073.6463706682292924.20326857717968.304796641
#Sta/Elev= 30
       0 1974.77      25  1973.5    46.4 1970.21    72.1 1964.66    93.4  1957.8
   131.9 1940.84   136.2 1939.83   155.3 1938.38   169.6 1938.25     184 1936.97
   217.4 1937.55     227 1937.16   245.5 1938.03   257.1 1936.78   295.8 1936.29
   323.6 1936.71   358.2 1935.47   370.4 1934.49     3751935.503   381.3 1937.94
   392.9 1939.31   419.2 1940.25   442.8 1939.41   451.7 1940.03   456.2 1941.28
   460.3 1941.45   478.3 1940.22   533.2 1941.03   560.4 1945.01   632.8 1948.07
#Mann= 7, -1 ,  0
       0     0.1       0  166.25    0.06       0  236.25    0.05       0
   358.2   0.045       0     375    0.05       0   488.1    0.06       0
   518.1    0.05       0
Bank Sta=358.2,375
XS Rating Curve= 0 ,0
Exp/Cntr(USF)=0,0
Exp/Cntr=0.3,0.1

Type RM Length L Ch R = 1 ,12471   ,401.9,401.9,401.9
XS GIS Cut Line= 2
2293669.62228517 718223.131432832292934.85805803717955.289428983
#Sta/Elev= 30
       0 2037.78    14.3 2035.22    35.6 2027.23    69.7 2018.37    82.4 2017.33
    99.5  2013.3   116.5 2008.33   134.2 2002.04   180.4 1983.21   205.5 1971.03
   221.1 1962.66   252.7 1942.38   261.2 1937.67   265.5 1936.07   273.8 1935.38
   297.7 1935.82   329.4 1935.24   393.2 1937.43     406 1936.99413.19331935.614
   423.9 1934.25   439.5 1934.37   445.7 1935.57   452.8 1936.31     530 1936.54
   576.3 1940.07   683.1 1940.29   699.8 1941.36   725.3 1944.48   782.1 1947.58
#Mann= 6, -1 ,  0
       0     0.1       0     340    0.06       0413.1933   0.045       0
   445.7    0.05       0     580    0.06       0     650    0.05       0
#XS Ineff= 2 , 0
          398.42 1945.94
Permanent Ineff=
       F       F
Bank Sta=413.1933,445.7
XS Rating Curve= 0 ,0
Exp/Cntr(USF)=0,0
Exp/Cntr=0.3,0.1

Type RM Length L Ch R = 1 ,12069   ,487.7,487.7,487.7
XS GIS Cut Line= 3
2293549.16344745717975.0795982392293277.74500554717800.408264558
2292887.53830665717749.432272165
#Sta/Elev= 30
       0 1987.81      25 1983.37      44 1979.07    91.6 1966.94   124.9 1955.62
   139.1 1949.27   152.6  1941.2   158.7 1939.59   167.1 1939.94   181.9 1938.06
   215.2 1936.96     258 1933.94   286.6 1932.89   300.8 1933.94   380.8 1934.64
   457.5 1933.97   509.9 1934.92   513.3 1933.93     518 1932.53     522 1932.49
   530.1 1932.53     534 1933.19     535 1933.94   542.2 1939.71   574.5 1941.45
   618.8 1946.81   648.2 1949.52   671.3 1952.99   698.1  1958.8   716.3 1962.05
#Mann= 6, -1 ,  0
       0     0.1       0     120    0.06       0     240    0.07       0
     280    0.05       0   513.3   0.045       0     535    0.05       0
Bank Sta=513.3,535
XS Rating Curve= 0 ,0
Exp/Cntr(USF)=0,0
Exp/Cntr=0.3,0.1