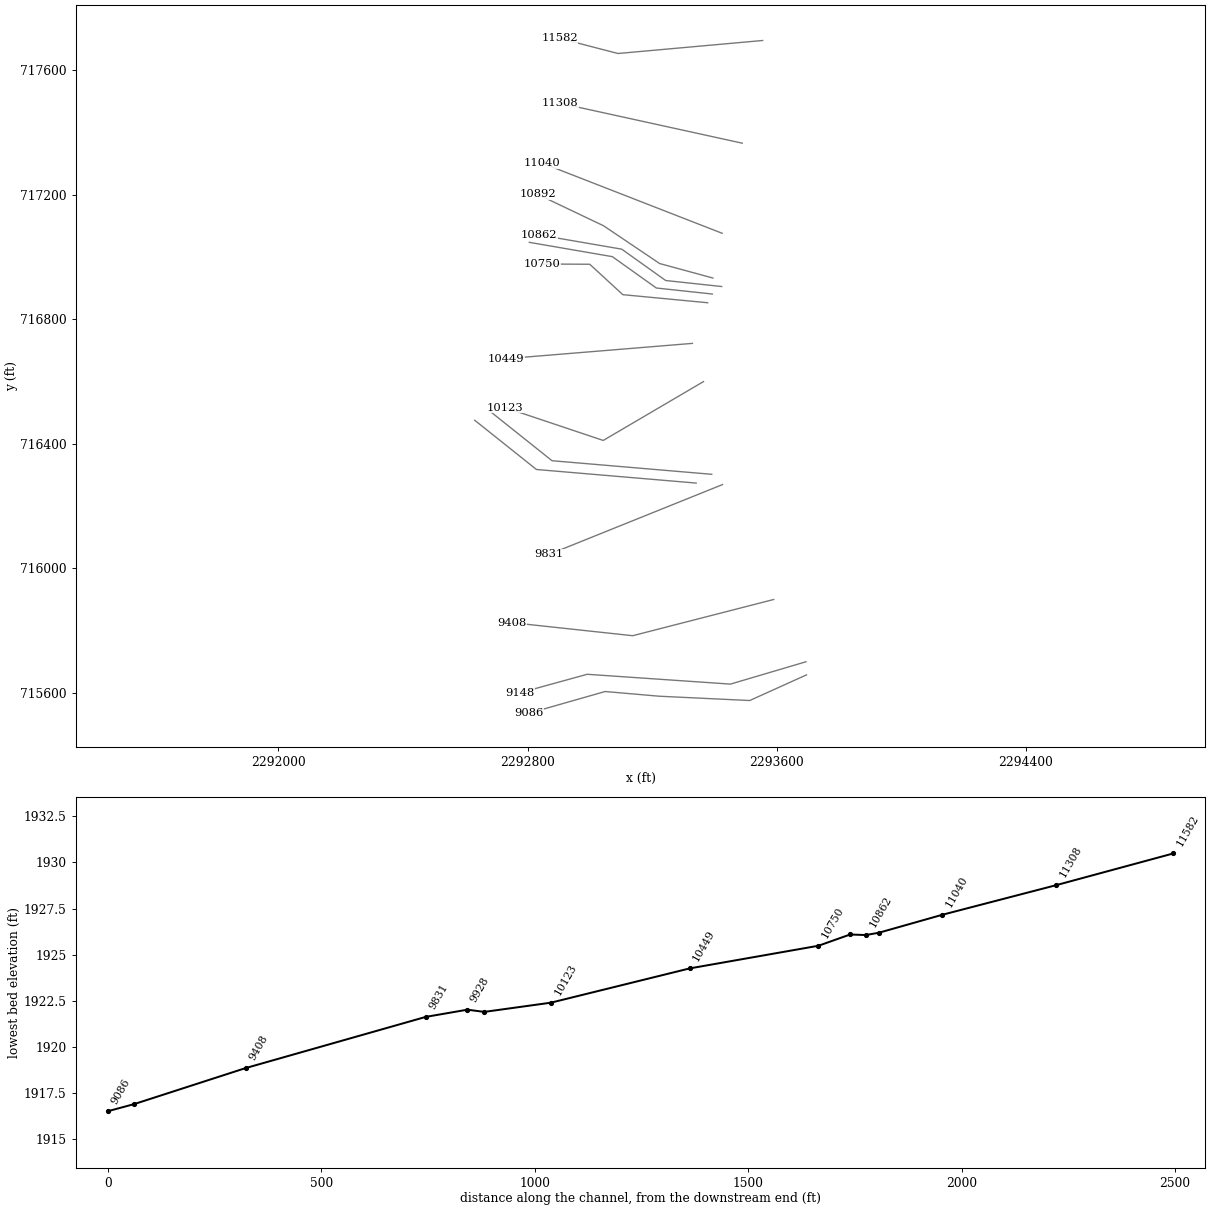
HEC-RAS study CLAYLCKRN.prj: CLAYLCKRN

--- CLAYLCKRN.g01 (geometry) --- (continued)

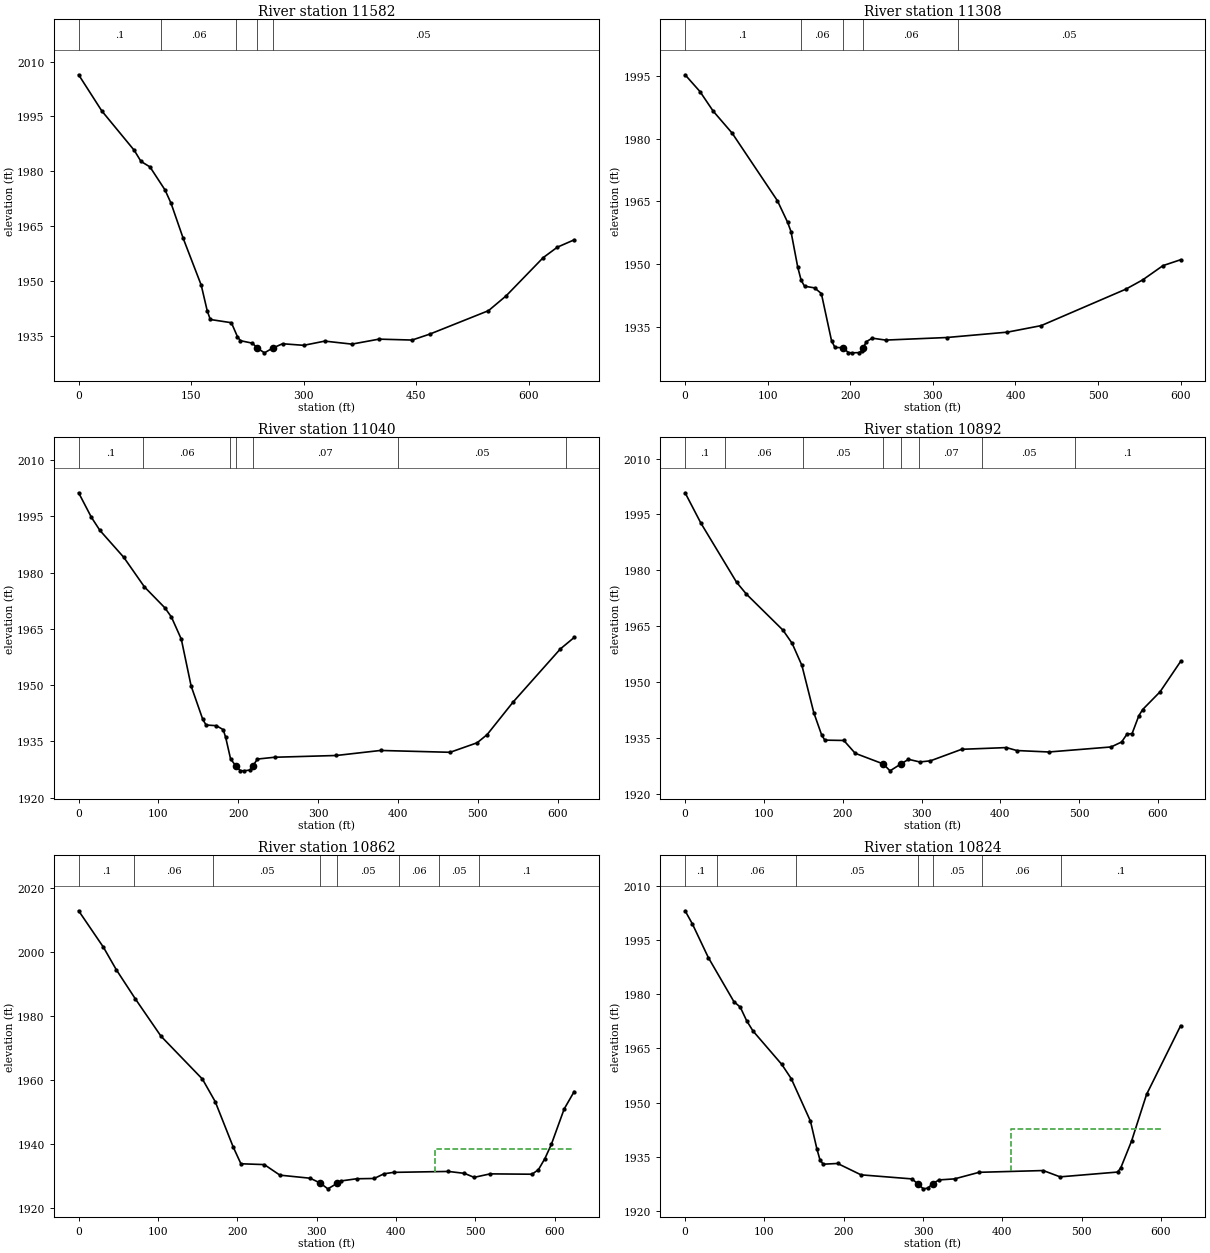
Type RM Length L Ch R = 1 ,11582   ,274.2,274.2,274.2
XS GIS Cut Line= 3
2293554.92596111717694.9300784822293090.44193458717653.111674777
2292902.56784372717701.832075862
#Sta/Elev= 30
       0 2006.38    30.9 1996.51    74.2 1985.74    83.1 1982.74    95.1 1981.23
   115.2 1974.93   123.2  1971.3   139.3 1961.78   163.4 1948.96   171.4 1941.96
   175.5 1939.59   203.6 1938.71   211.6 1934.94   215.6 1933.81   231.7 1933.12
   238.21931.774   247.7 1930.49   258.51931.772   271.8 1932.97     300 1932.54
   328.1 1933.69   364.2 1932.87   400.4 1934.23   444.5 1933.98   468.3 1935.62
   546.3    1942   569.9 1946.06   619.2 1956.47   638.1 1959.33   660.5 1961.33
#Mann= 5, -1 ,  0
       0     0.1       0     110    0.06       0     210    0.05       0
   238.2   0.045       0   258.5    0.05       0
Bank Sta=238.2,258.5
XS Rating Curve= 0 ,0
Exp/Cntr(USF)=0,0
Exp/Cntr=0.3,0.1

Type RM Length L Ch R = 1 ,11308   ,267.2,267.2,267.2
XS GIS Cut Line= 2
2293489.37136458717364.9679704322292903.31324482717493.559884112
#Sta/Elev= 30
       0 1995.25      18 1991.24      34 1986.56      57 1981.29   111.8 1965.13
   124.1 1959.99   128.2 1957.78   136.4 1949.25   140.5 1946.13   144.6  1944.7
   156.8  1944.3     165 1942.94   177.3 1931.67   181.4 1930.07   190.71929.985
   197.8 1928.85   201.9 1928.77   210.1 1928.82   214.2 1929.31   215.71929.994
   219.5 1931.44   226.5 1932.28   242.8 1931.82   316.6 1932.43   390.3 1933.72
   431.2 1935.28   533.6 1943.99   554.1 1946.22   578.6 1949.62     600 1951.03
#Mann= 5, -1 ,  0
       0     0.1       0     140    0.06       0   190.7   0.045       0
   215.7    0.06       0     330    0.05       0
Bank Sta=190.7,215.7
XS Rating Curve= 0 ,0
Exp/Cntr(USF)=0,0
Exp/Cntr=0.3,0.1

Type RM Length L Ch R = 1 ,11040   ,147.9,147.9,147.9
XS GIS Cut Line= 2
2293424.91254641717075.4199896942292846.63704579717300.911065408
#Sta/Elev= 30
       0 2001.24    15.9 1994.74    26.6 1991.23    56.6 1984.03    82.4 1976.17
   108.1 1970.57   116.2 1968.14   128.6 1962.25   140.9 1949.77   155.4 1940.92
   159.6 1939.37   172.5 1939.19   181.1 1938.13   184.2 1936.05   190.3 1930.36
   197.11928.413   202.6 1927.22   206.9 1927.16   215.1 1927.38     2181928.411
     224  1930.3   245.5 1930.78   322.8 1931.25   378.2 1932.59   465.3  1932.1
   499.2 1934.64   511.7 1936.82   544.3 1945.51   603.4 1959.64   620.7 1962.69
#Mann= 7, -1 ,  0
       0     0.1       0      80    0.06       0     190    0.07       0
   197.1   0.045       0     218    0.07       0     400    0.05       0
     610     0.1       0
Bank Sta=197.1,218
XS Rating Curve= 0 ,0
Exp/Cntr(USF)=0,0
Exp/Cntr=0.3,0.1

Type RM Length L Ch R = 1 ,10892   ,30.9,30.9,30.9
XS GIS Cut Line= 4
2293395.18697274716931.6826406372293224.19775113716978.246669736
2293044.04839265717099.6184832882292832.60189985717200.379988879
#Sta/Elev= 30
       0 2000.81      20 1992.68    65.3  1976.8    77.7 1973.63   124.2 1963.94
   135.8  1960.4   148.2 1954.47   163.3 1941.79   173.1  1935.9   177.2 1934.43
   201.4 1934.34   215.8  1930.9   251.4 1928.04     260 1926.19   273.61928.006
   283.4 1929.28   297.8 1928.57   311.3 1928.88   350.9 1931.97   407.6 1932.43
   420.9 1931.64   461.5 1931.25   540.5  1932.6   553.8 1933.93   560.6 1936.03
   567.1 1936.19   575.6 1940.94   580.4 1942.62   602.6  1947.4   628.7 1955.56
#Mann= 8, -1 ,  0
       0     0.1       0      50    0.06       0     150    0.05       0
   251.4   0.045       0   273.6    0.05       0  297.22    0.07       0
  377.22    0.05       0  494.44     0.1       0
Bank Sta=251.4,273.6
XS Rating Curve= 0 ,0
Exp/Cntr(USF)=0,0
Exp/Cntr=0.3,0.1

Type RM Length L Ch R = 1 ,10862   ,37.1,37.1,37.1
XS GIS Cut Line= 4
2293423.34034928716904.3786439962293243.52179228716923.717614962
2293102.30301551717024.4791205532292835.74565762717070.434969219
#Sta/Elev= 30
       0    2013    31.3 2001.59    47.4 1994.61    71.6 1985.42   103.8  1973.8
   156.1 1960.37   172.2 1953.33   194.8  1939.2   204.6  1933.9   234.1 1933.64
   253.8 1930.34   291.9 1929.38   304.7 1927.86   314.2 1926.06   326.2 1927.81
   330.6 1928.52   350.6 1929.21   372.7  1929.3   384.9 1930.76   397.1 1931.21
   466.1  1931.5   486.4  1930.9   498.6 1929.65   518.9 1930.74   571.6 1930.63
   579.7 1932.04   587.9 1935.53     596 1939.94   612.2 1951.04   624.8 1956.47
#Mann= 8, -1 ,  0
       0     0.1       0      70    0.06       0     170    0.05       0
   304.7   0.045       0   326.2    0.05       0  404.34    0.06       0
  454.34    0.05       0  504.34     0.1       0
#XS Ineff= 2 , 0
                          449.52         1938.67
Permanent Ineff=
       F       F
Bank Sta=304.7,326.2
XS Rating Curve= 0 ,0
Exp/Cntr(USF)=0,0
Exp/Cntr=0.3,0.1

Type RM Length L Ch R = 1 ,10824   ,74.1,74.1,74.1
XS GIS Cut Line= 4
2293393.32948178716880.2831906192293213.51092478716899.622161585
  2293072.292148717000.3836671762292805.73479011717046.339515842
#Sta/Elev= 30
       0 2003.15     9.2  1999.5    29.3 1990.18    61.5 1977.98    69.6 1976.43
    77.6 1972.68    85.6 1969.84   121.9 1960.57   133.9  1956.6   158.1 1944.82
   166.1 1937.23   170.1 1934.08   174.2 1932.92   192.3 1933.12   221.8 1929.97
   286.2 1928.84   293.7  1927.4   300.4 1926.09   306.2 1926.29     312 1927.52
   320.1 1928.56   339.7 1928.85   370.7 1930.67   451.6 1931.16   472.8 1929.41
   545.2 1930.74   549.3 1931.89   562.9 1939.32   581.8 1952.24   624.8  1971.3
#Mann= 7, -1 ,  0
       0     0.1       0      40    0.06       0     140    0.05       0
   293.7   0.045       0     312    0.05       0  374.34    0.06       0
  474.34     0.1       0
#XS Ineff= 1 ,-1
  411.08     600  1942.6
Permanent Ineff=
       F
Bank Sta=293.7,312
XS Rating Curve= 0 ,0
Exp/Cntr(USF)=0,0
Exp/Cntr=0.3,0.1

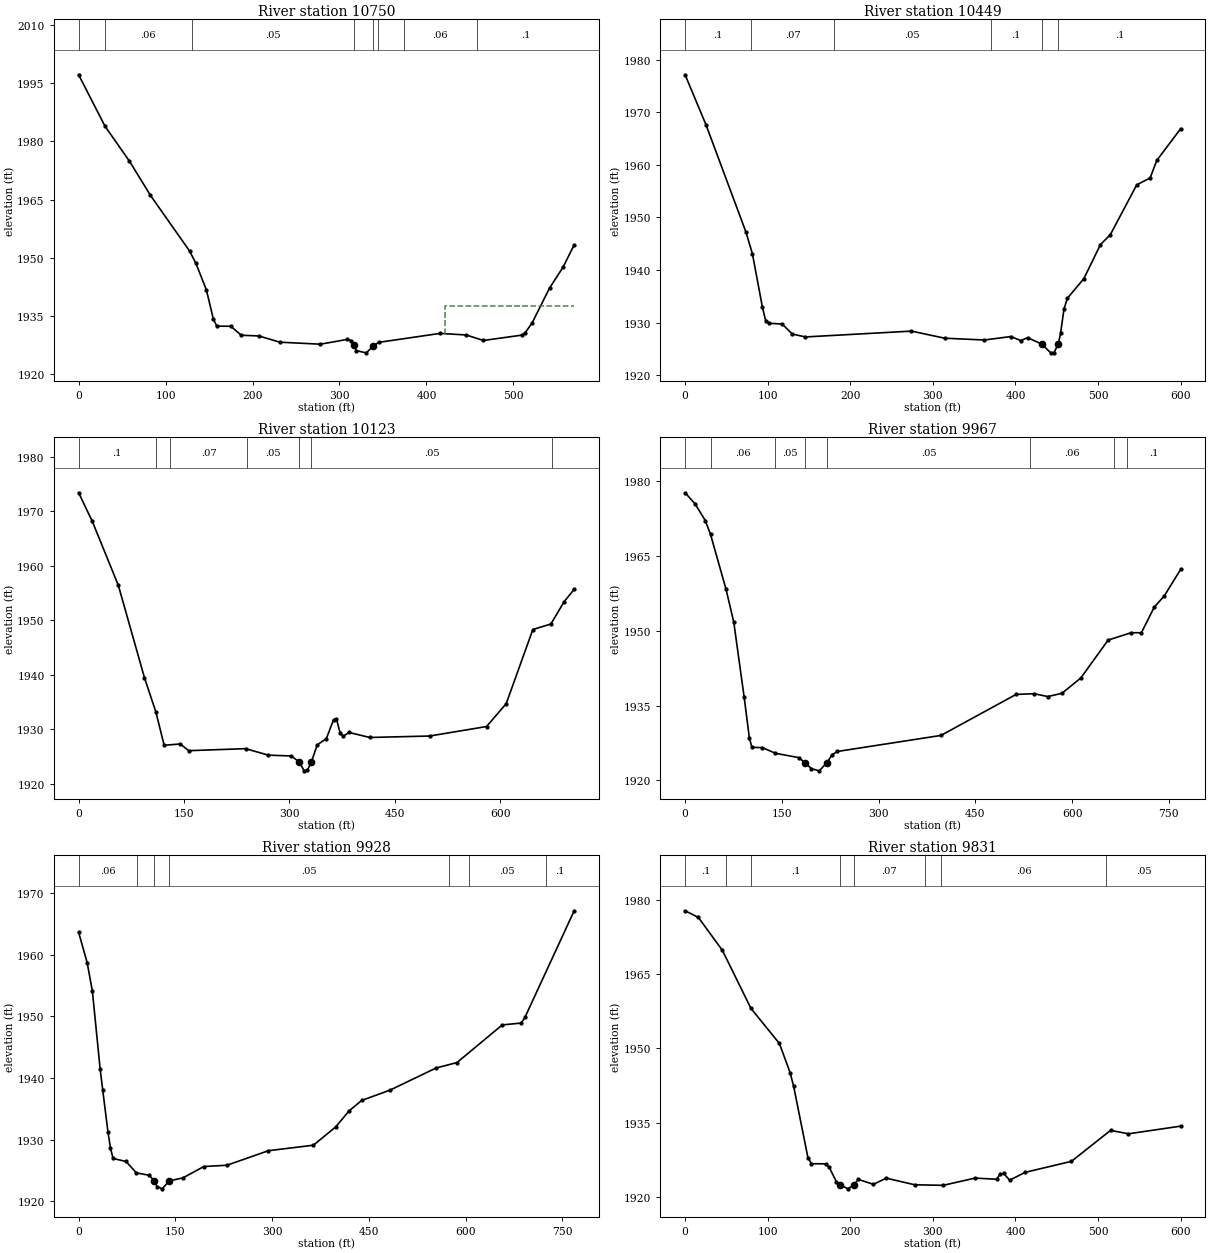
Type RM Length L Ch R = 1 ,10750   ,301.7,301.7,301.7
XS GIS Cut Line= 4
2293378.39338847716852.2947877472293105.87931653716878.248508884
2292999.77439777716975.9566355182292847.86879464716976.719980257
#Sta/Elev= 30
       0 1997.17    30.4 1983.88    58.5 1974.88    82.6 1966.08   127.6 1951.73
   134.9 1948.54   146.9 1941.73   154.9 1934.22   158.9 1932.36     175 1932.33
   187.1 1930.01   207.2 1929.84   231.3 1928.23   278.1 1927.71   308.7 1928.93
   313.5 1928.65   316.7  1927.4   319.5 1926.03   330.8 1925.48   339.11927.248
     345 1928.18   415.7 1930.49   445.6 1930.09   465.6 1928.67   509.6 1930.04
   513.6 1930.67   521.6 1933.22   541.6 1942.19   557.1 1947.56   569.9 1953.32
#Mann= 8, -1 ,  0
       0     0.1       0      30    0.06       0     130    0.05       0
   316.7   0.045       0   339.1    0.05       0  343.75     0.1       0
  373.75    0.06       0  457.99     0.1       0
#XS Ineff= 2 , 0
                          421.25         1937.64
Permanent Ineff=
       F       F
Bank Sta=316.7,339.1
XS Rating Curve= 0 ,0
Exp/Cntr(USF)=0,0
Exp/Cntr=0.3,0.1

Type RM Length L Ch R = 1 ,10449   ,325.2,325.2,325.2
XS GIS Cut Line= 2
2293329.39024705716721.7270351072292731.40534019716672.594040345
#Sta/Elev= 30
       0  1977.1    25.3  1967.6    73.5 1947.28    81.5 1943.09    93.5 1933.02
    97.5 1930.37   101.6 1929.87   117.6 1929.72   129.7 1927.83   145.7 1927.27
   274.1 1928.38   314.3 1927.03   362.4 1926.69   394.5 1927.35   406.6 1926.57
   414.6 1927.14   431.9 1925.91   442.7 1924.25   446.7 1924.28   451.91925.944
   454.7 1928.03   458.8 1932.62   462.8 1934.61   482.8 1938.35   502.9 1944.82
   514.9 1946.72   546.8 1956.17   563.1  1957.5   571.1 1960.82     600 1966.85
#Mann= 6, -1 ,  0
       0     0.1       0      80    0.07       0     180    0.05       0
     370     0.1       0   431.9   0.045       0   451.9     0.1       0
Bank Sta=431.9,451.9
XS Rating Curve= 0 ,0
Exp/Cntr(USF)=0,0
Exp/Cntr=0.3,0.1

Type RM Length L Ch R = 1 ,10123   ,156,156,156
XS GIS Cut Line= 3
2293364.90282465716598.9791684292293043.03249883716409.857621056
2292728.43607868716515.329253245
#Sta/Elev= 30
       0 1973.41    19.4 1968.18    56.5 1956.42    93.6 1939.51     110 1933.15
   121.7 1927.08   144.7 1927.32   156.7 1926.09   237.5 1926.46   269.9 1925.27
   302.8 1925.12   313.81923.999     321 1922.39   325.6  1922.5   331.11923.992
   339.5 1927.15   352.5 1928.31   362.7 1931.75   366.8 1931.93     372 1929.38
   376.3 1928.73   384.8 1929.43   414.3 1928.51   499.5 1928.78   580.4 1930.52
   608.4 1934.72   646.3 1948.32     672 1949.34     691 1953.46   705.1  1955.7
#Mann= 7, -1 ,  0
       0     0.1       0     110    0.06       0     130    0.07       0
     240    0.05       0   313.8   0.045       0   331.1    0.05       0
  673.32     0.1       0
Bank Sta=313.8,331.1
XS Rating Curve= 0 ,0
Exp/Cntr(USF)=0,0
Exp/Cntr=0.3,0.1

Type RM Length L Ch R = 1 ,9967    ,39.4,39.4,39.4
XS GIS Cut Line= 3
 2293391.3997816716301.074458705  2292878.589432716344.717892714
2292680.37550254716502.925340997
#Sta/Elev= 30
       0 1977.72    15.3 1975.53    31.3 1972.15    39.4 1969.37    63.5 1958.33
    75.5 1951.72    91.6 1936.64    99.6 1928.54   103.6  1926.6   119.7 1926.56
     140 1925.42   175.9 1924.55   185.91923.541   195.9 1922.33     208 1921.89
   219.91923.535     228 1925.12   236.1 1925.78   396.7    1929   513.1 1937.23
   541.1 1937.38   562.2  1936.8   584.3 1937.46   613.5 1940.53   655.9 1948.15
   691.8 1949.63   707.4 1949.61   727.3 1954.74   742.9 1957.01   768.3 1962.33
#Mann= 8, -1 ,  0
       0     0.1       0      40    0.06       0     140    0.05       0
   185.9   0.045       0   219.9    0.05       0  534.66    0.06       0
  664.66    0.05       0  684.66     0.1       0
Bank Sta=185.9,219.9
XS Rating Curve= 0 ,0
Exp/Cntr(USF)=0,0
Exp/Cntr=0.3,0.1

Type RM Length L Ch R = 1 ,9928    ,97.4,97.4,97.4
XS GIS Cut Line= 3
2293341.39168013716272.8880742412292828.58133053 716316.53150825
2292630.36740107716474.738956533
#Sta/Elev= 30
       0 1963.64    13.3 1958.67    21.3  1954.1    33.3 1941.52    37.4    1938
    45.4 1931.31    49.4 1928.61    53.4 1926.94    73.5 1926.45    89.5  1924.6
   109.6 1924.21   117.11923.293   121.7 1922.38   129.7 1922.01   140.41923.299
   161.8 1923.79   194.1 1925.63     230 1925.84   294.3  1928.2     364 1929.09
   398.7 1932.07   419.4 1934.67   438.8 1936.35     483 1938.04   554.2 1941.62
   586.6  1942.5   656.8 1948.61   686.2 1948.91   691.9 1949.82   768.3 1967.13
#Mann= 7, -1 ,  0
       0    0.06       0      90    0.05       0   117.1   0.045       0
   140.4    0.05       0  574.66    0.06       0  604.66    0.05       0
  724.66     0.1       0
Bank Sta=117.1,140.4
XS Rating Curve= 0 ,0
Exp/Cntr(USF)=0,0
Exp/Cntr=0.3,0.1

Type RM Length L Ch R = 1 ,9831    ,422.3,422.3,422.3
XS GIS Cut Line= 2
2293426.05924061716268.0660275542292869.53528671716043.831577186
#Sta/Elev= 30
       0 1977.81      16 1976.48    45.2  1969.8    79.7 1958.09   114.2 1950.99
   127.1 1945.12   131.4 1942.36   148.7 1927.95     153  1926.7   170.2 1926.67
   174.5 1925.97   183.2 1923.05   188.1 1922.41   197.3 1921.62   204.7 1922.47
   209.6 1923.53   228.1 1922.53   243.5 1923.78     278 1922.44   312.5 1922.33
     351 1923.79   377.2 1923.56   381.5 1924.61   385.8 1924.73     393 1923.37
   411.7 1924.95   467.8 1927.18   515.2 1933.44   536.8 1932.74     600 1934.29
#Mann= 8, -1 ,  0
       0     0.1       0      50    0.05       0      80     0.1       0
   188.1   0.045       0   204.7    0.07       0     290    0.05       0
     310    0.06       0     510    0.05       0
Bank Sta=188.1,204.7
XS Rating Curve= 0 ,0
Exp/Cntr(USF)=0,0
Exp/Cntr=0.3,0.1

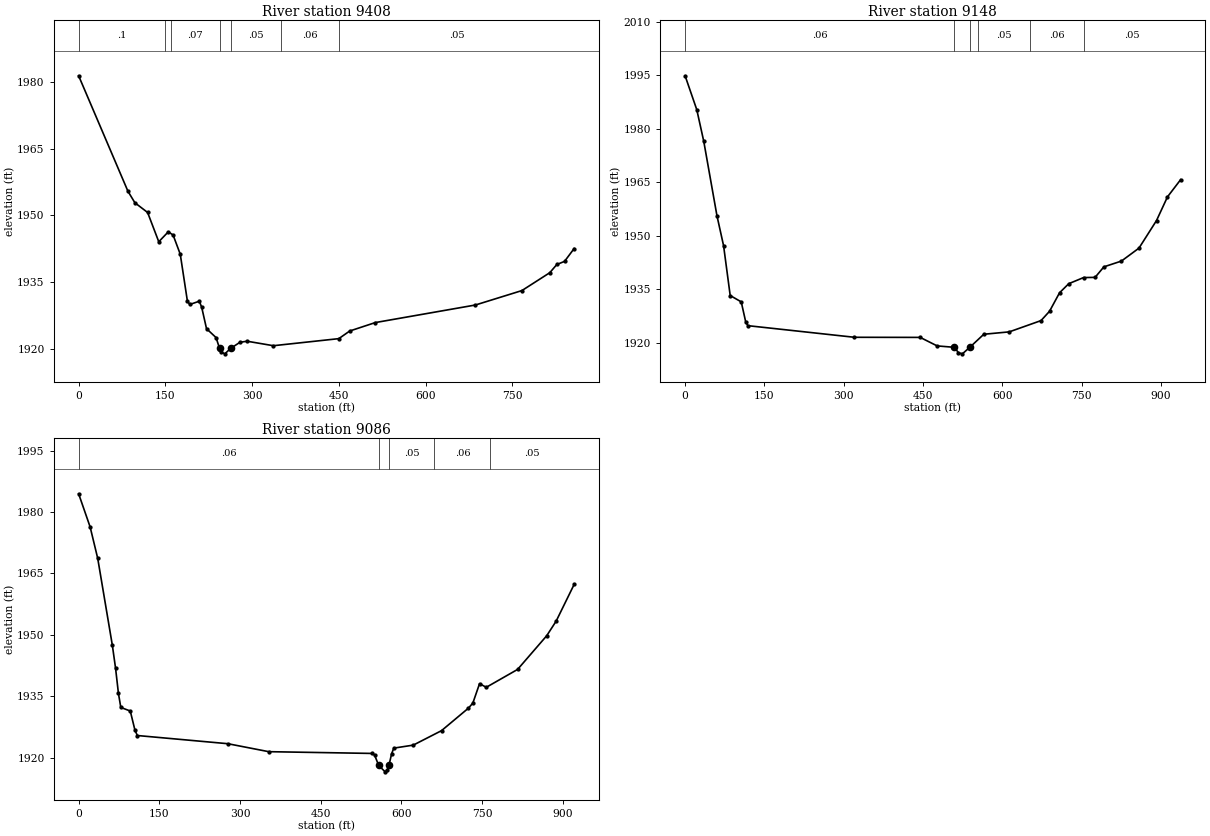
Type RM Length L Ch R = 1 ,9408    ,260.5,260.5,260.5
XS GIS Cut Line= 3
2293590.39390036715898.8657478662293137.59327252715782.483257176
2292750.25779569715824.308214768
#Sta/Elev= 30
       0 1981.43    85.3 1955.43    97.3 1952.85   119.3 1950.66   138.6 1944.07
   155.1 1946.31   163.4 1945.58   175.8 1941.26   188.1 1930.73   192.3 1929.95
   208.8 1930.69   212.9  1929.3   221.2  1924.5   237.7  1922.5   243.81920.049
     246  1919.3   252.9 1918.84   262.71920.043     279 1921.44   291.4 1921.68
   336.8 1920.67     450 1922.26   468.9 1923.98   513.2 1925.88   686.2 1929.83
   766.7 1933.08   814.9  1937.1   827.1 1938.95   840.4 1939.65   857.1 1942.55
#Mann= 7, -1 ,  0
       0     0.1       0     150    0.06       0     160    0.07       0
   243.8   0.045       0   262.7    0.05       0     350    0.06       0
     450    0.05       0
Bank Sta=243.8,262.7
XS Rating Curve= 0 ,0
Exp/Cntr(USF)=0,0
Exp/Cntr=0.3,0.1

Type RM Length L Ch R = 1 ,9148    ,62.2,62.2,62.2
XS GIS Cut Line= 4
2293694.01209027715698.7682852372293451.34044908715626.980925372
 2292991.5759644715658.5360081782292776.18405101715599.194896527
#Sta/Elev= 30
       0 1994.85    22.1 1985.34    35.3 1976.47    60.3 1955.58    72.8  1947.2
    85.3 1933.24   106.2 1931.46   114.5 1925.94   118.6 1924.79   320.4 1921.53
   444.7  1921.5   476.8 1919.11   509.5 1918.72     517  1917.2   524.5 1916.89
539.62231918.872     565 1922.38   613.1 1923.05   673.2 1926.21   689.3 1928.82
   708.3 1934.02   725.7 1936.56   753.6 1938.27   775.5 1938.33   792.1 1941.28
   825.3  1942.9   858.5 1946.53   891.7 1954.27   912.4  1960.9   937.3 1965.73
#Mann= 6, -1 ,  0
       0    0.06       0   509.5   0.045       0539.6223    0.06       0
  553.07    0.05       0  653.07    0.06       0  753.91    0.05       0
Bank Sta=509.5,539.6223
XS Rating Curve= 0 ,0
Exp/Cntr(USF)=0,0
Exp/Cntr=0.3,0.1

Type RM Length L Ch R = 1 ,9086    ,33.9,33.9,33.9
XS GIS Cut Line= 5
2293695.64097016715656.6368132682293513.34012119 715574.23689526
2293222.31737498 715588.09512127 2293049.0305395715603.162138828
2292803.03696622715532.939523795
#Sta/Elev= 30
       0 1984.49    21.4 1976.37    35.5 1968.68    62.7 1947.43    68.7 1941.79
      74 1935.68    78.4 1932.25      96 1931.37   104.8 1926.63   109.2 1925.38
   277.3 1923.38   353.4 1921.43   545.8    1921   550.1 1920.64   557.8 1918.06
   569.8  1916.5   573.9 1916.85577.10521918.213   581.9 1920.95   585.9  1922.3
     622 1923.03   674.6 1926.57   724.5 1932.06   732.8  1933.3   745.3 1938.06
   757.8 1937.17     816 1941.54   870.1 1949.77   887.7 1953.35   921.2 1962.34
#Mann= 5, -1 ,  0
       0    0.06       0   557.8   0.045       0577.1052    0.05       0
  661.41    0.06       0  765.35    0.05       0
Bank Sta=557.8,577.1052
XS Rating Curve= 0 ,0
Exp/Cntr(USF)=0,0
Exp/Cntr=0.3,0.1