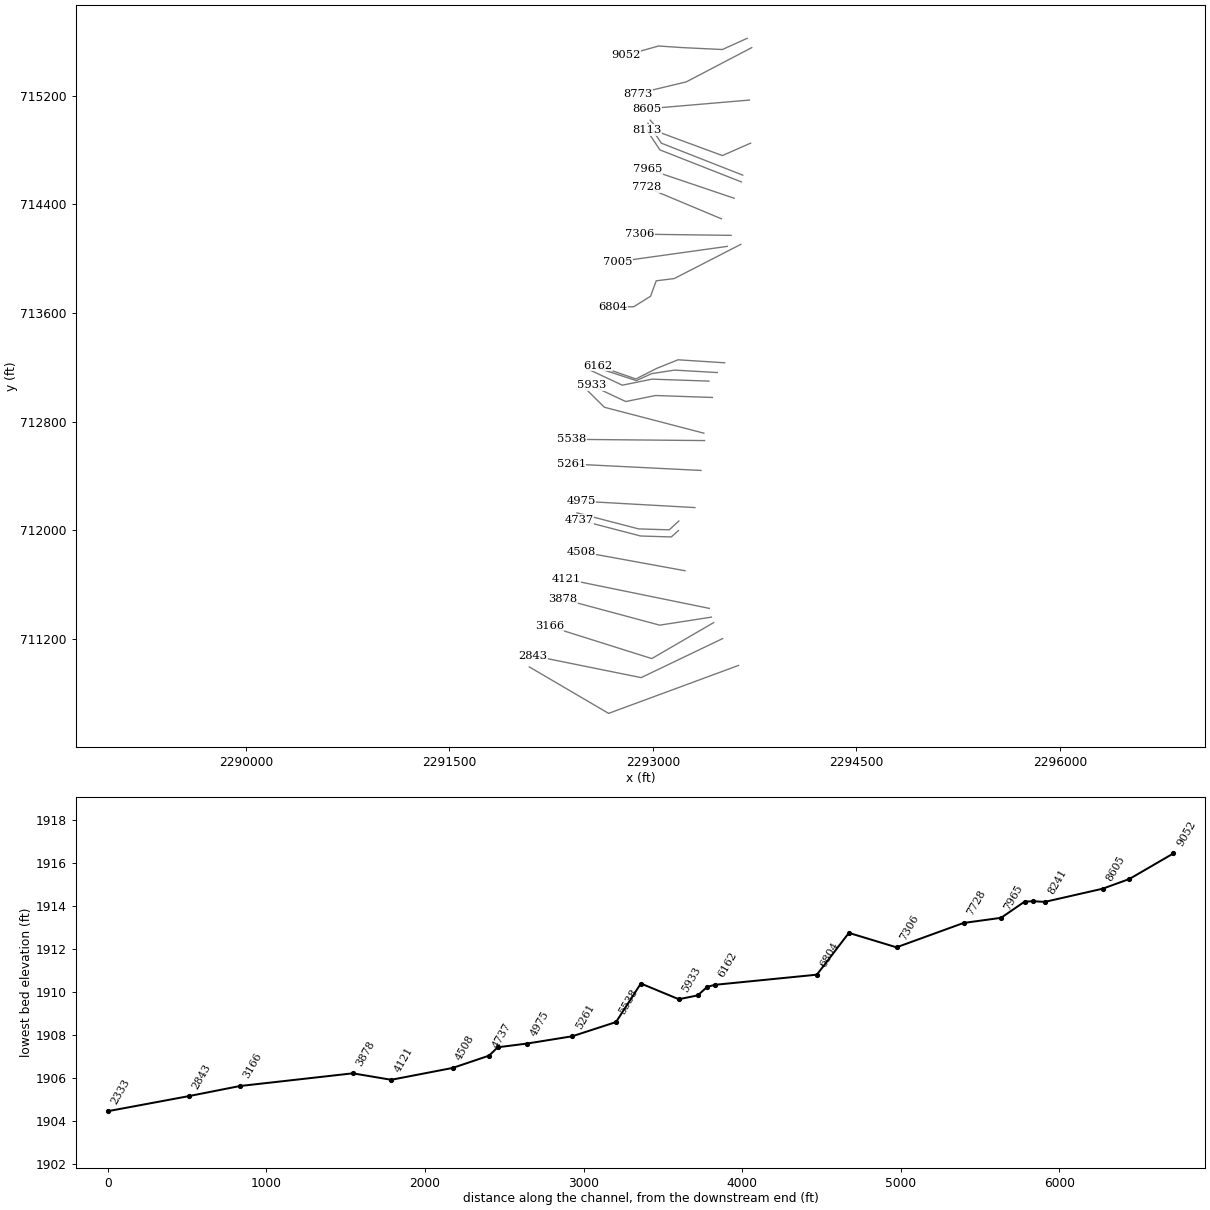
HEC-RAS study CLAYLCKRN.prj: CLAYLCKRN

--- CLAYLCKRN.g01 (geometry) --- (continued)

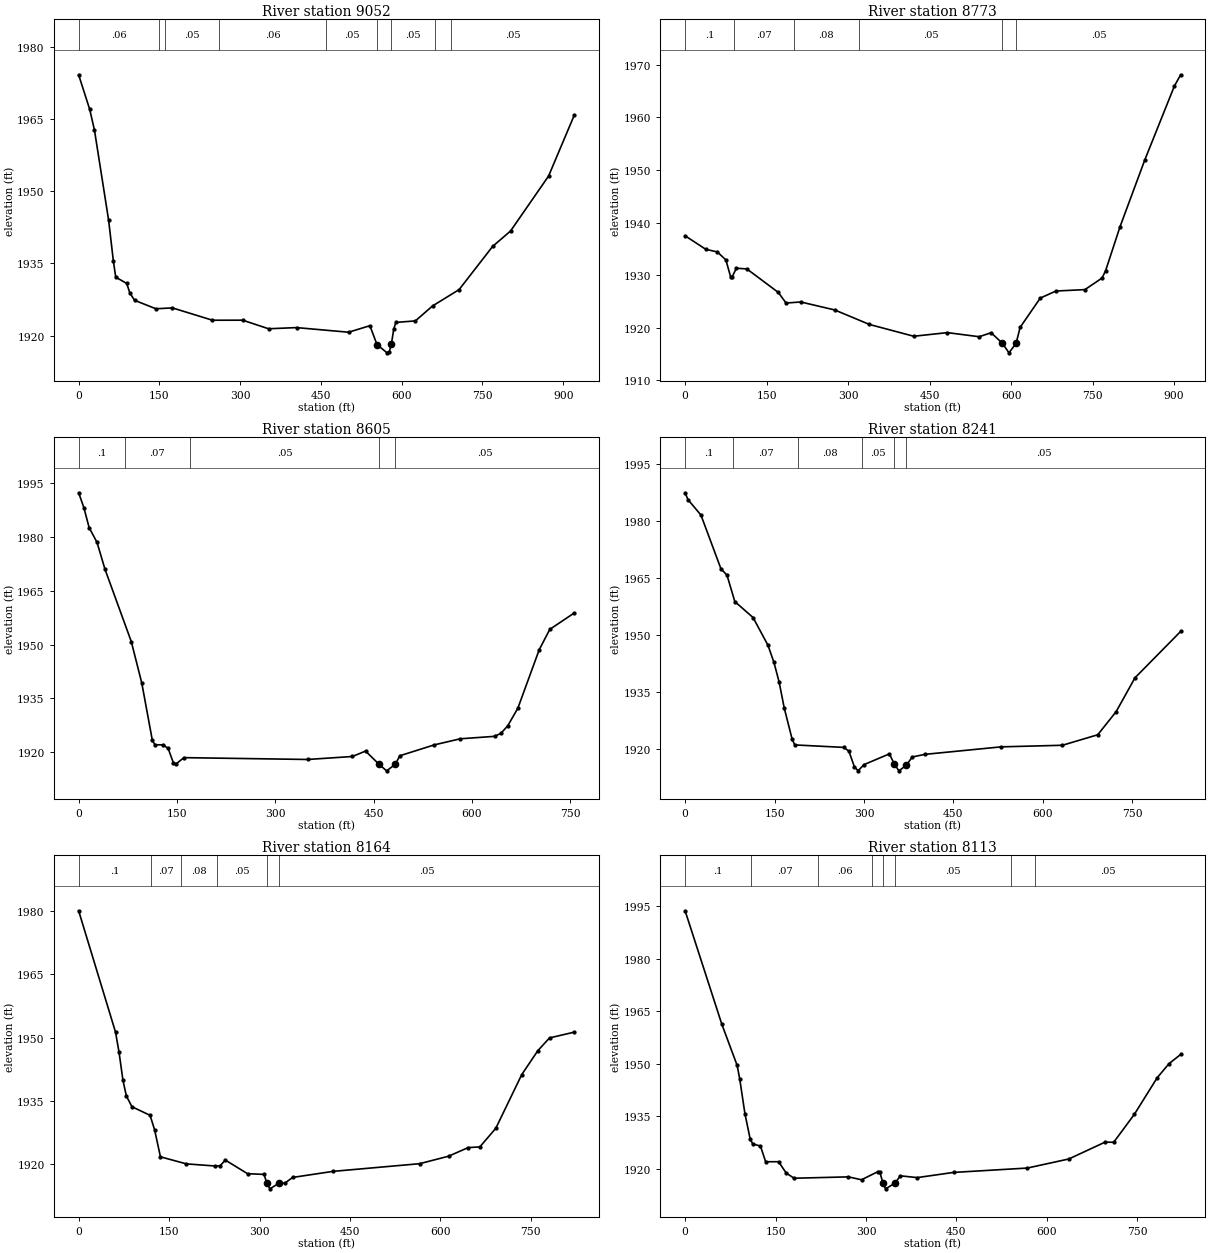
Type RM Length L Ch R = 1 ,9052    ,278.3,278.3,278.3
XS GIS Cut Line= 5
2293694.94611135715624.5268277012293512.64526238715542.126909693
2293221.62251617715555.9851357042293042.22892278715567.998774305
2292802.34210742715500.829538229
#Sta/Elev= 30
       0 1974.17    20.6 1966.97    29.4 1962.68    55.7 1943.97    64.5 1935.51
    68.9 1932.15    89.3 1930.85    95.3 1928.82     104 1927.34   143.5 1925.59
   174.2 1925.77   248.6 1923.21   304.6 1923.22   352.7 1921.44   404.8 1921.68
   501.4 1920.72     541 1922.08     554 1918.17   572.8 1916.44     577  1916.7
580.77251918.197   585.1 1921.32   589.1 1922.76   625.4 1923.07   657.2 1926.17
   706.6 1929.57   768.9 1938.54   802.1 1941.73   872.7 1953.13   920.3 1965.73
#Mann= 9, -1 ,  0
       0    0.06       0     150    0.07       0     160    0.05       0
  260.06    0.06       0  460.06    0.05       0     554   0.045       0
580.7725    0.05       0  661.41    0.06       0  691.21    0.05       0
Bank Sta=554,580.7725
XS Rating Curve= 0 ,0
Exp/Cntr(USF)=0,0
Exp/Cntr=0.3,0.1

Type RM Length L Ch R = 1 ,8773    ,168.7,168.7,168.7
XS GIS Cut Line= 3
2293728.83358814715555.9851357032293246.56732299 715303.76542232
2292889.02509193715217.844421057
#Sta/Elev= 30
       0 1937.48    38.1 1934.91    59.4 1934.41    75.1 1932.89    83.7 1929.71
    86.5 1929.66    94.4 1931.32   113.6 1931.19   171.5 1926.73   185.8 1924.71
   212.9 1924.91   275.2  1923.4   339.3 1920.64   420.8  1918.4   482.7 1919.09
   541.2 1918.31   563.2 1919.07   583.91917.077   596.1 1915.25   609.21917.068
   616.6 1920.09   653.7 1925.65   682.5 1926.99   735.9 1927.26   767.3 1929.45
   773.9 1930.85   800.4 1939.19   846.3 1951.96   900.5 1965.92     912 1968.06
#Mann= 6, -1 ,  0
       0     0.1       0      90    0.07       0     200    0.08       0
     320    0.05       0   583.9   0.045       0   609.2    0.05       0
Bank Sta=583.9,609.2
XS Rating Curve= 0 ,0
Exp/Cntr(USF)=0,0
Exp/Cntr=0.3,0.1

Type RM Length L Ch R = 1 ,8605    ,363.5,363.5,363.5
XS GIS Cut Line= 2
2293712.15927266715169.6473894472292959.07272661 715105.32943499
#Sta/Elev= 30
       0 1992.36       8 1988.21      16 1982.65    28.1  1978.5    40.1 1971.08
    80.3 1950.86    96.3  1939.3   112.4 1923.33   116.4 1922.06   128.5 1922.06
   136.5 1921.07   144.5 1917.04   148.5 1916.71   160.6 1918.48   349.3 1917.97
   417.5  1918.8   437.6 1920.31   458.21916.632   469.7  1914.8   483.21916.651
   489.8    1919     542 1922.02   582.1 1923.74   634.3 1924.42     644 1925.25
   654.4 1927.33   669.9 1932.27   702.5 1948.59   718.6 1954.26   755.8 1958.82
#Mann= 5, -1 ,  0
       0     0.1       0      70    0.07       0     170    0.05       0
   458.2   0.045       0   483.2    0.05       0
Bank Sta=458.2,483.2
XS Rating Curve= 0 ,0
Exp/Cntr(USF)=0,0
Exp/Cntr=0.3,0.1

Type RM Length L Ch R = 1 ,8241    ,77.4,77.4,77.4
XS GIS Cut Line= 4
2293720.51865254714851.9872543912293512.64526238714760.522962724
2293069.18203006714924.050029643 2292980.4893836715021.057611714
#Sta/Elev= 30
       0 1987.36     4.7 1985.59    26.6 1981.49    60.1 1967.37    70.3 1965.67
    83.4 1958.73     114 1954.53     139 1947.24     149 1942.74   157.7 1937.57
   166.4 1930.65   179.5 1922.55   183.9 1921.01     266 1920.36   274.7 1919.39
     284 1915.22   290.3 1914.22   300.1 1915.83   342.7 1918.65   351.2 1915.87
   358.8 1914.19   371.3 1915.71   381.1 1917.84   402.4 1918.53   530.1  1920.5
   632.9 1920.92   692.1 1923.68     723 1929.76   754.6 1938.67   831.2 1950.87
#Mann= 6, -1 ,  0
       0     0.1       0      80    0.07       0     190    0.08       0
  297.11    0.05       0   351.2   0.045       0   371.3    0.05       0
Bank Sta=351.2,371.3
XS Rating Curve= 0 ,0
Exp/Cntr(USF)=0,0
Exp/Cntr=0.3,0.1

Type RM Length L Ch R = 1 ,8164    ,50.4,50.4,50.4
XS GIS Cut Line= 3
2293662.50389509714616.1959867382293062.57946688714851.938790736
2292963.66972058714999.085875579
#Sta/Elev= 30
       0 1980.04    61.2 1951.31      67 1946.58    73.5 1939.92    79.2 1936.18
    88.5 1933.65   118.5 1931.62     126 1928.19   135.7  1921.8   178.7 1920.13
     226 1919.63   234.6 1919.66   243.3 1921.03   280.2  1917.8   307.6 1917.64
   311.9 1915.67   317.3 1914.22   332.7  1915.6     342 1915.56   354.9 1916.92
   422.2 1918.36   565.5 1920.17   613.5 1921.94   646.1 1923.99   665.4 1924.14
   691.9 1928.55   734.9 1941.25   761.7 1946.94     781 1949.94   821.9 1951.31
#Mann= 6, -1 ,  0
       0     0.1       0     120    0.07       0     170    0.08       0
     230    0.05       0   311.9   0.045       0   332.7    0.05       0
Bank Sta=311.9,332.7
XS Rating Curve= 0 ,0
Exp/Cntr(USF)=0,0
Exp/Cntr=0.3,0.1

Type RM Length L Ch R = 1 ,8113    ,148.1,148.1,148.1
XS GIS Cut Line= 3
2293652.47658706714566.3548367572293052.55215885714802.097640755
2292953.64241256714949.244725598
#Sta/Elev= 30
       0 1993.65      61 1961.19    86.3 1949.48    90.6 1945.62    99.2 1935.71
   107.8 1928.54   112.1 1927.04     125 1926.42   133.6 1921.94     155 1921.95
   167.9 1918.68   180.8 1917.23   270.8 1917.62   292.6 1916.79   320.2 1919.15
   322.7 1919.09   328.3 1915.83   332.5  1914.2   348.2 1915.83     357 1917.92
     385 1917.41   445.2 1918.89   567.6 1920.14   636.4 1922.73   696.5 1927.54
   710.9 1927.51   745.1 1935.48   783.2 1945.99   802.7 1949.98   821.9 1952.59
#Mann= 8, -1 ,  0
       0     0.1       0     110    0.07       0     220    0.06       0
     310    0.05       0   328.3   0.045       0   348.2    0.05       0
     540     0.1       0     580    0.05       0
Bank Sta=328.3,348.2
XS Rating Curve= 0 ,0
Exp/Cntr(USF)=0,0
Exp/Cntr=0.3,0.1

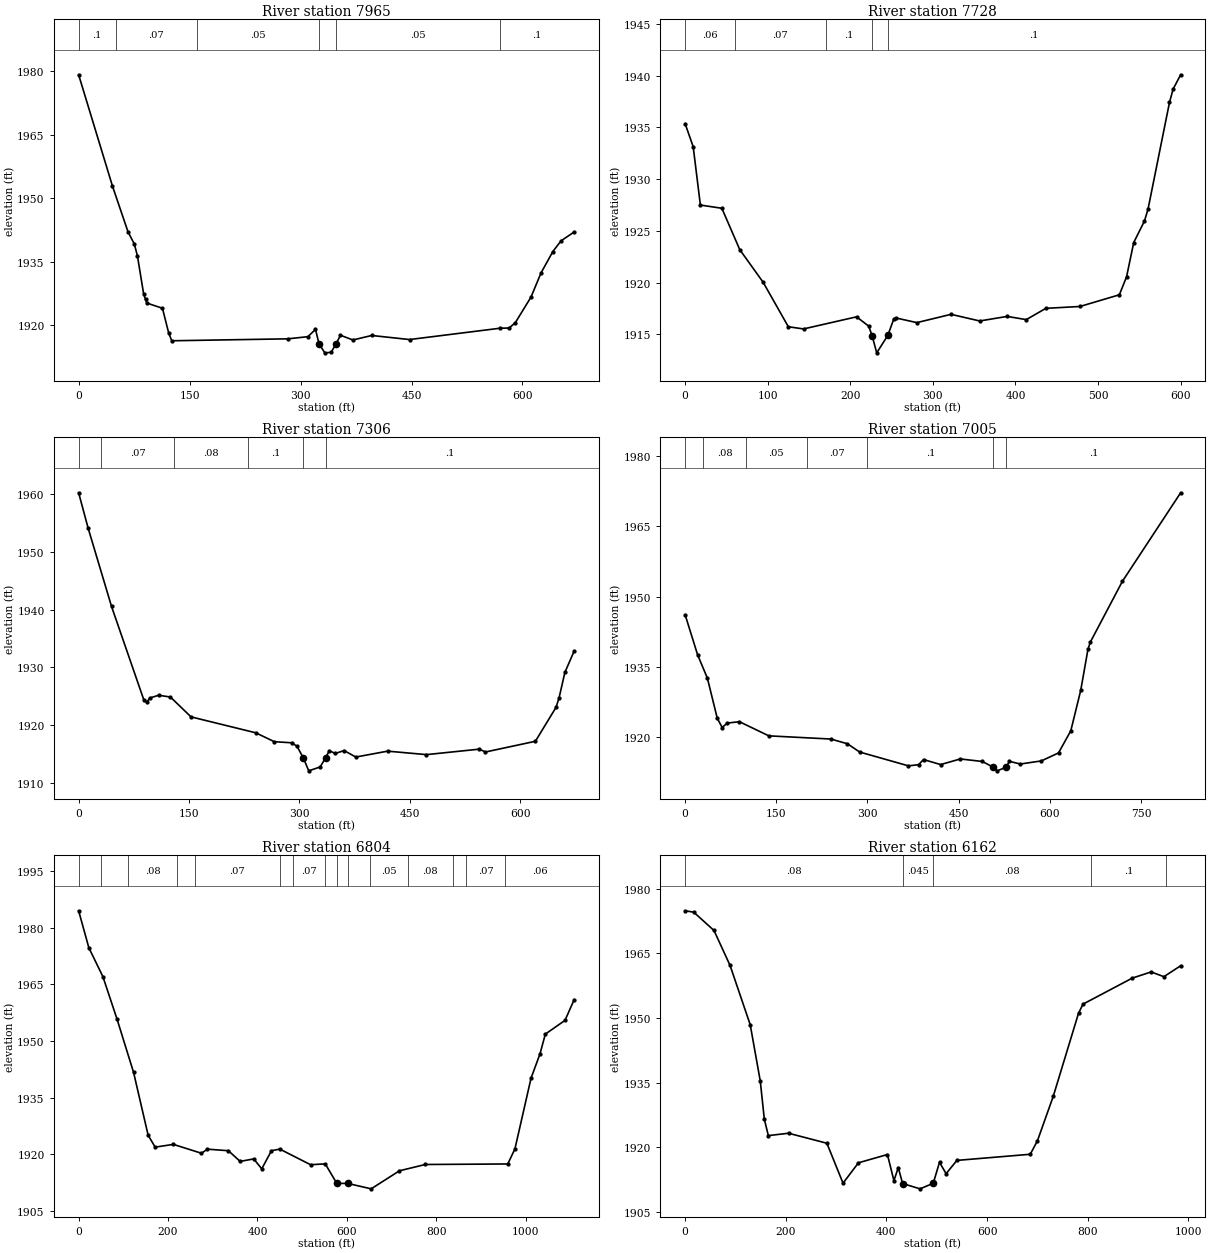
Type RM Length L Ch R = 1 ,7965    ,237,237,237
XS GIS Cut Line= 2
2293599.48628245714445.903090648 2292964.8380129714660.483307859
#Sta/Elev= 30
       0 1979.13    45.7 1952.86    66.8    1942    75.3 1939.16    79.5 1936.32
    87.9 1927.35    90.4 1926.08    92.2 1925.21   113.3 1923.98   121.7 1918.17
   125.9  1916.3   282.9 1916.76     310 1917.27   320.2 1918.99     3251915.572
   332.8 1913.45   341.3 1913.56     3481915.585     354  1917.6   370.8 1916.49
   396.2 1917.55   447.3 1916.59     570 1919.27     582 1919.31   590.4 1920.59
   611.5 1926.61   625.2 1932.36   641.1 1937.38   652.1  1939.9   669.9    1942
#Mann= 6, -1 ,  0
       0     0.1       0      50    0.07       0     160    0.05       0
     325   0.045       0     348    0.05       0     570     0.1       0
Bank Sta=325,348
XS Rating Curve= 0 ,0
Exp/Cntr(USF)=0,0
Exp/Cntr=0.3,0.1

Type RM Length L Ch R = 1 ,7728    ,422.4,422.4,422.4
XS GIS Cut Line= 2
2293505.21036371714294.6056400062292951.75255765714526.304705432
#Sta/Elev= 30
       0 1935.36     9.8 1933.13    18.5 1927.49    44.5 1927.18    66.2 1923.18
    94.5 1920.03     125 1915.73   143.4 1915.52   207.6 1916.69   222.3 1915.79
   226.41914.876     232 1913.21   245.41914.887   252.6 1916.46   255.3 1916.58
   280.6 1916.13     322 1916.93   356.7 1916.29   389.9 1916.73   413.1 1916.42
   436.8 1917.51   478.1 1917.69   525.8 1918.82   534.5 1920.55   543.2 1923.87
   556.2 1925.95   560.5 1927.09   586.5 1937.41   590.9  1938.7     600 1940.08
#Mann= 5, -1 ,  0
       0    0.06       0      60    0.07       0     170     0.1       0
   226.4   0.045       0   245.4     0.1       0
Bank Sta=226.4,245.4
XS Rating Curve= 0 ,0
Exp/Cntr(USF)=0,0
Exp/Cntr=0.3,0.1

Type RM Length L Ch R = 1 ,7306    ,300.2,300.2,300.2
XS GIS Cut Line= 2
2293576.82772326714172.5494717322292903.43507065714181.239779762
#Sta/Elev= 30
       0 1960.25    12.7 1954.22    44.7 1940.56    88.7 1924.33    92.7 1923.95
    96.7  1924.7   108.7 1925.17   124.7 1924.87   152.7 1921.43   240.7 1918.67
   265.9 1917.13   289.6 1916.94   296.7 1916.34   305.31914.331   312.7 1912.08
   328.3 1912.76   335.51914.335   340.7 1915.56   348.8 1915.09   360.7 1915.59
   376.7 1914.47   419.9 1915.49   472.7 1914.89   544.7 1915.84   552.7 1915.34
   620.7  1917.2   648.7 1923.07   652.9 1924.74   660.8 1929.14   673.4 1932.83
#Mann= 6, -1 ,  0
       0    0.08       0      30    0.07       0     130    0.08       0
     230     0.1       0   305.3   0.045       0   335.5     0.1       0
Bank Sta=305.3,335.5
XS Rating Curve= 0 ,0
Exp/Cntr(USF)=0,0
Exp/Cntr=0.3,0.1

Type RM Length L Ch R = 1 ,7005    ,201.7,201.7,201.7
XS GIS Cut Line= 2
2293548.56894277714091.300189325 2292741.1654136713978.554651468
#Sta/Elev= 30
       0 1946.14    20.6 1937.55    36.7 1932.55    52.9    1924      61 1922.01
    69.1 1922.95    89.3 1923.26   137.7 1920.23   239.7 1919.55     267 1918.54
   287.2 1916.77   367.3 1913.82   384.1 1914.06   392.2 1915.16   420.4 1914.09
   452.7 1915.29   489.1 1914.75   506.81913.531   513.3 1912.75   528.11913.524
   533.5 1914.78   551.5 1914.21     586 1914.87   614.3 1916.58   634.5 1921.31
   650.8 1929.94   662.8 1938.77   666.8 1940.31   719.3 1953.25   815.2  1972.2
#Mann= 7, -1 ,  0
       0    0.07       0      30    0.08       0     100    0.05       0
     200    0.07       0     300     0.1       0   506.8   0.045       0
   528.1     0.1       0
Bank Sta=506.8,528.1
XS Rating Curve= 0 ,0
Exp/Cntr(USF)=0,0
Exp/Cntr=0.3,0.1

Type RM Length L Ch R = 1 ,6804    ,641.5,641.5,641.5
XS GIS Cut Line= 6
2293648.45063149714106.3300715842293157.87467652713854.194981665
2293024.83570683713837.565110452 2292983.2610288 713723.92765717
2292858.53699471713646.3215915132292703.65330876713644.313574911
#Sta/Elev= 30
       0 1984.49    22.8 1974.71    54.3 1967.03    85.8 1955.82   122.9 1941.66
   155.5    1925   171.2 1921.86     212 1922.59   274.7 1920.24   288.1 1921.32
     335 1920.91   361.3 1918.08   391.6 1918.74   409.6 1916.11   431.3 1920.91
     450 1921.34   518.8  1917.2   551.6 1917.43   577.5 1912.25   601.7 1912.25
   654.3 1910.81   717.7  1915.6   775.5 1917.26   959.9  1917.4   975.9  1921.4
  1011.9 1940.12    1032 1946.59  1043.9 1951.81  1087.9 1955.45  1108.4 1960.94
#Mann= 15, -1 ,  0
       0    0.08       0      50    0.07       0     110    0.08       0
     220    0.05       0     260    0.07       0     450    0.05       0
     480    0.07       0  551.58    0.08       0   577.5   0.045       0
   601.7    0.08       0  651.58    0.05       0  735.65    0.08       0
  836.65    0.05       0  866.65    0.07       0  953.55    0.06       0
Bank Sta=577.5,601.7
XS Rating Curve= 0 ,0
Exp/Cntr(USF)=0,0
Exp/Cntr=0.3,0.1

Type RM Length L Ch R = 1 ,6162    ,49,49,49
XS GIS Cut Line= 5
2293529.27513359713233.3464564132293185.59112854713255.519618029
2293027.60735203713191.7717783822292875.16686592713114.165712726
 2292592.9567646713212.306205392
#Sta/Elev= 30
       0 1974.85    17.1 1974.53    57.4 1970.28    89.3 1962.18   129.4 1948.41
   149.4 1935.33   157.4  1926.5   165.4 1922.69   205.5 1923.24   281.7 1920.92
   313.8 1911.65   344.4 1916.38     402  1918.3   414.9 1912.24   423.6 1915.27
432.11831911.577   466.7 1910.34493.01831911.619   505.5  1916.5   518.6 1913.86
   540.1 1916.94   685.8 1918.36     700 1921.47   731.4 1931.77   781.7 1951.07
   790.6 1953.19   888.5 1959.23     926 1960.66   951.3 1959.56   984.6 1962.09
#Mann= 5, -1 ,  0
       0    0.08       0432.1183   0.045       0493.0183    0.08       0
  805.82     0.1       0  955.82    0.08       0
Bank Sta=432.1183,493.0183
XS Rating Curve= 0 ,0
Exp/Cntr(USF)=0,0
Exp/Cntr=0.3,0.1

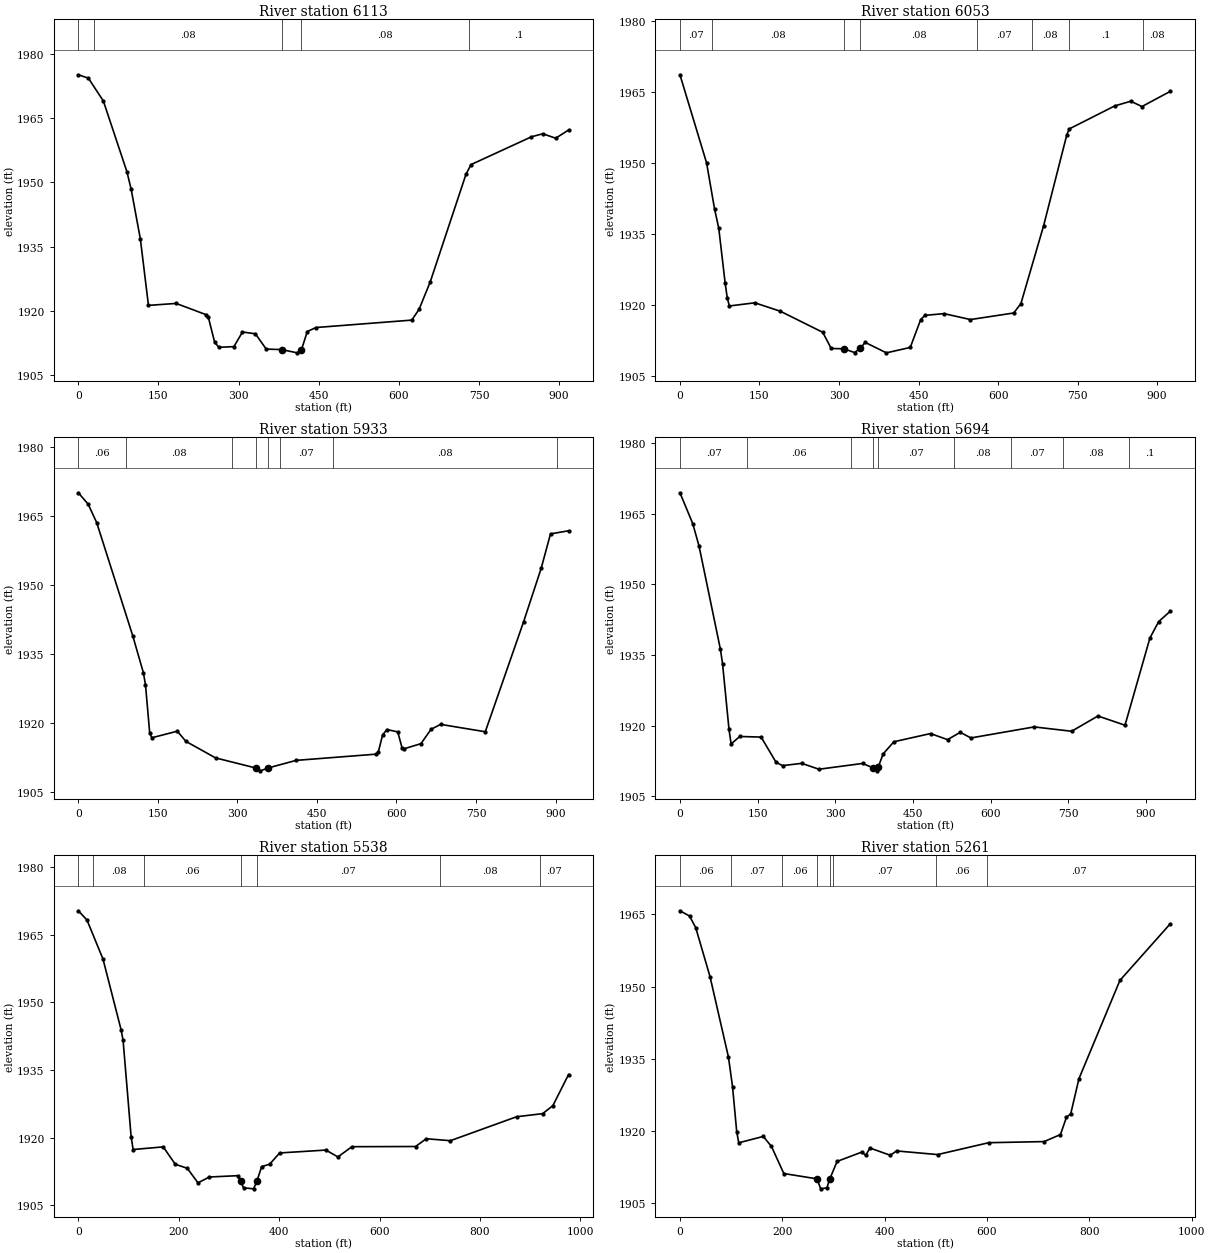
Type RM Length L Ch R = 1 ,6113    ,60.2,60.2,60.2
XS GIS Cut Line= 5
2293474.91390414713161.3988758342293159.73515843713179.482902228
 2292991.8120562713153.6485788092292878.14103316713101.979931971
2292586.21317853713197.566928621
#Sta/Elev= 30
       0 1975.07    18.8 1974.28    46.8 1968.95    90.9 1952.47    98.9 1948.35
   116.1 1936.76   131.2 1921.31     183 1921.77   239.1 1919.15   243.1 1918.67
   255.2 1912.68   263.2 1911.54   291.2  1911.7   307.2 1915.11   331.4 1914.69
   351.7 1911.12   380.5 1911.01   409.8 1910.25   417.6 1910.95   428.6 1915.22
   444.8 1916.15   624.1 1917.88   637.8 1920.39   658.6 1926.75   725.5 1951.83
     735 1954.13   848.2 1960.61   869.3 1961.32   893.6 1960.28   917.6 1962.19
#Mann= 5, -1 ,  0
       0    0.07       0      30    0.08       0   380.5   0.045       0
   417.6    0.08       0  730.46     0.1       0
Bank Sta=380.5,417.6
XS Rating Curve= 0 ,0
Exp/Cntr(USF)=0,0
Exp/Cntr=0.3,0.1

Type RM Length L Ch R = 1 ,6053    ,119.8,119.8,119.8
XS GIS Cut Line= 4
2293413.31562542713098.4654470882292993.89801929713112.779890125
2292774.93804834713068.4335668932292519.94668975713187.614310579
#Sta/Elev= 30
       0 1968.59    50.2 1949.99    65.2 1940.29    73.2 1936.18    85.2 1924.65
    89.2 1921.48    93.2 1919.75   141.2 1920.42   189.3 1918.64   269.3 1914.19
   285.3 1910.77   309.3 1910.71   329.3 1909.91   340.4 1910.83   349.3 1912.06
   389.4 1909.85   434.4 1910.99   454.1 1916.88   462.2 1917.77   498.3 1918.13
   547.9 1916.88   629.6 1918.27   643.1 1920.26   685.9  1936.7   729.8 1955.96
   734.4 1957.16   820.2 1962.02   850.3    1963   871.4 1961.88   924.5 1965.07
#Mann= 8, -1 ,  0
       0    0.07       0      60    0.08       0   309.3   0.045       0
   340.4    0.08       0  559.66    0.07       0  663.07    0.08       0
  733.07     0.1       0  873.07    0.08       0
Bank Sta=309.3,340.4
XS Rating Curve= 0 ,0
Exp/Cntr(USF)=0,0
Exp/Cntr=0.3,0.1

Type RM Length L Ch R = 1 ,5933    ,239.2,239.2,239.2
XS GIS Cut Line= 4
2293438.71002255  712977.89888082293019.29241642712992.213323837
2292800.33244547712947.8670006052292545.34108688713067.047744292
#Sta/Elev= 30
       0 1970.01    18.5 1967.53    34.6 1963.53   102.6 1938.97   122.6 1930.98
   126.6 1928.35   134.6 1917.84   138.6 1916.85   186.6 1918.27     203 1916.05
   258.7 1912.48   334.9 1910.28   343.2 1909.67   357.8 1910.29   410.8 1911.94
   561.6 1913.29   565.7 1913.74   573.8 1917.46     582 1918.63   602.4 1918.12
   610.6 1914.62   614.7 1914.47   646.2 1915.57   665.2 1918.69   683.3 1919.75
   767.5 1918.15   839.8 1942.04   872.9 1953.62   890.5 1961.09   924.5 1961.76
#Mann= 8, -1 ,  0
       0    0.06       0      90    0.08       0     290    0.06       0
   334.9   0.045       0   357.8    0.06       0     380    0.07       0
  479.66    0.08       0  903.07     0.1       0
Bank Sta=334.9,357.8
XS Rating Curve= 0 ,0
Exp/Cntr(USF)=0,0
Exp/Cntr=0.3,0.1

Type RM Length L Ch R = 1 ,5694    ,156.5,156.5,156.5
XS GIS Cut Line= 3
2293375.81368315712714.7135416222292642.96768708712905.653565411
2292508.40043222713038.402343856
#Sta/Elev= 30
       0 1969.47    24.7 1962.92    36.8 1958.18    78.2 1936.18    82.3 1933.11
    94.7 1919.21    98.8  1916.1   115.4  1917.7   156.7 1917.57   185.6 1912.21
     198 1911.51   235.2 1911.99   268.3 1910.74   352.6 1911.97   372.3 1911.06
   379.9  1910.4   382.71911.172   392.3 1913.99     413 1916.58   483.8 1918.32
   516.6 1917.03   541.1 1918.58   561.8 1917.39   683.8 1919.73   756.1 1918.81
     807 1922.05   859.2 1920.09   907.3 1938.61   924.2  1942.1   946.3 1944.28
#Mann= 9, -1 ,  0
       0    0.07       0     130    0.06       0     330    0.07       0
   372.3   0.045       0   382.7    0.07       0     530    0.08       0
     640    0.07       0     740    0.08       0  867.31     0.1       0
Bank Sta=372.3,382.7
XS Rating Curve= 0 ,0
Exp/Cntr(USF)=0,0
Exp/Cntr=0.3,0.1

Type RM Length L Ch R = 1 ,5538    ,276.2,276.2,276.2
XS GIS Cut Line= 2
 2293381.2691124712660.1592491112292404.74727645712669.251631196
#Sta/Elev= 30
       0 1970.36    17.1 1968.32    49.1 1959.63    85.1 1943.95    89.1 1941.59
   105.1 1920.23   109.1 1917.34   169.1 1917.93   193.1 1914.07   217.1 1913.17
   238.3 1909.95   261.1 1911.24   317.1 1911.53   323.1  1910.3   329.1 1908.84
   349.1 1908.61   355.81910.332   365.1 1913.54   381.1 1914.08   401.1 1916.58
   493.1 1917.22   517.1  1915.7   545.1 1917.97   671.9 1918.01   693.1 1919.74
   741.1  1919.3   873.1 1924.62   925.1 1925.31   945.4 1927.09   976.6 1933.98
#Mann= 7, -1 ,  0
       0    0.07       0      30    0.08       0     130    0.06       0
   323.1   0.045       0   355.8    0.07       0     720    0.08       0
     920    0.07       0
Bank Sta=323.1,355.8
XS Rating Curve= 0 ,0
Exp/Cntr(USF)=0,0
Exp/Cntr=0.3,0.1

Type RM Length L Ch R = 1 ,5261    ,286.6,286.6,286.6
XS GIS Cut Line= 2
2293354.89403242712440.0157183932292398.14876031712487.560239872
#Sta/Elev= 30
       0 1965.74    18.7 1964.66    30.8 1962.24    58.8 1952.04    94.8 1935.33
   102.8 1929.16   110.9 1919.86   114.9 1917.52   162.9 1918.84   178.9 1916.75
     203 1911.13   267.81910.029   275.1 1907.95   287.1 1908.16     2931910.044
   307.1 1913.65   355.2 1915.58   363.2 1914.93   371.2 1916.44   411.2 1914.92
   423.2 1915.83   503.5 1915.07   603.5 1917.54   711.6 1917.77   743.6 1919.23
   755.3 1922.82   763.7 1923.55   779.7 1930.83   859.8 1951.27   957.9    1963
#Mann= 8, -1 ,  0
       0    0.06       0     100    0.07       0     200    0.06       0
   267.8   0.045       0     293    0.06       0     300    0.07       0
     500    0.06       0     600    0.07       0
Bank Sta=267.8,293
XS Rating Curve= 0 ,0
Exp/Cntr(USF)=0,0
Exp/Cntr=0.3,0.1

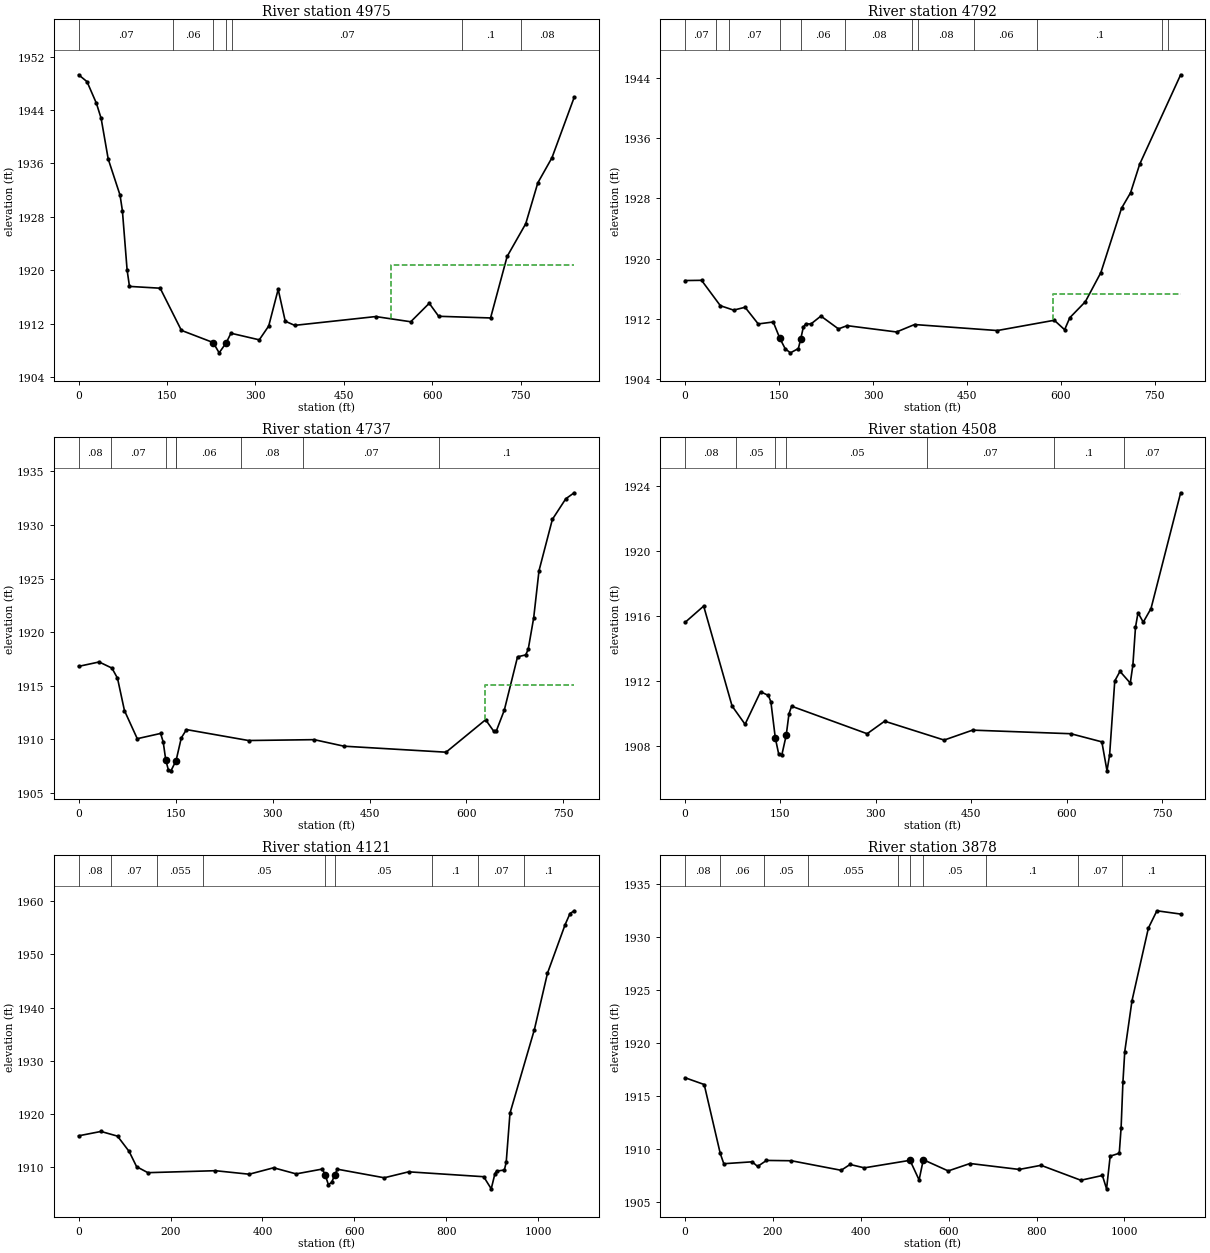
Type RM Length L Ch R = 1 ,4975    ,182.8,182.8,182.8
XS GIS Cut Line= 2
2293310.31516264712166.2630536362292470.50666642 712213.38102207
#Sta/Elev= 30
       0  1949.3    14.2 1948.27    30.2 1945.02    38.2 1942.76    50.2 1936.67
    70.3 1931.25    74.3 1928.91    82.3 1920.01    86.3 1917.57   138.4  1917.3
   174.4 1910.98   228.4 1909.15   238.5 1907.61   250.5 1909.12   258.5 1910.55
   306.6 1909.56   322.6 1911.63   338.7 1917.13   350.7 1912.35   366.7 1911.73
   504.3 1913.05   563.7 1912.27   595.1 1915.04   611.1 1913.09   699.2 1912.84
   727.3 1922.06   758.9 1926.97   779.4  1933.1   803.4 1936.86   841.1 1945.91
#Mann= 7, -1 ,  0
       0    0.07       0     160    0.06       0   228.4   0.045       0
   250.5    0.06       0     260    0.07       0     650     0.1       0
     750    0.08       0
#XS Ineff= 2 , 0
                          529.68          1920.8
Permanent Ineff=
       F       F
Bank Sta=228.4,250.5
XS Rating Curve= 0 ,0
Exp/Cntr(USF)=0,0
Exp/Cntr=0.3,0.1

Type RM Length L Ch R = 1 ,4792    ,55.1,55.1,55.1
XS GIS Cut Line= 4
2293191.42276813712067.451383712 2293121.2255369712002.312398008
 2292895.3877797712009.1559664082292440.81221828712127.463195479
#Sta/Elev= 30
       0 1917.07    26.3  1917.1    56.3 1913.72    77.5 1913.13    95.8 1913.51
   116.8 1911.29   140.8 1911.55151.35751909.361   159.9 1907.98   168.2 1907.44
   180.9 1908.01184.75751909.331   188.9 1910.88   192.9 1911.31   200.9 1911.28
   216.9 1912.34   244.9 1910.63   258.8 1911.06   337.7 1910.22   366.4 1911.21
   498.6 1910.41   589.6 1911.78   606.1 1910.52   614.4 1912.12   639.2 1914.25
     664 1918.13     697  1926.7   711.4 1928.76     726 1932.57   791.4 1944.48
#Mann= 12, -1 ,  0
       0    0.07       0      50    0.06       0      70    0.07       0
151.3575   0.045       0184.7575    0.06       0  255.76    0.08       0
  361.71    0.07       0  371.71    0.08       0  461.71    0.06       0
  561.71     0.1       0  761.71    0.08       0  771.71     0.1       0
#XS Ineff= 2 , 0
                           587.9         1915.26
Permanent Ineff=
       F       F
Bank Sta=151.3575,184.7575
XS Rating Curve= 0 ,0
Exp/Cntr(USF)=0,0
Exp/Cntr=0.3,0.1

Type RM Length L Ch R = 1 ,4737    ,229.2,229.2,229.2
XS GIS Cut Line= 4
2293188.91224197711997.1566512042293135.97885065711949.944309653
2292910.14109345711956.7878780532292455.56553203712075.095107125
#Sta/Elev= 30
       0  1916.8    31.7 1917.21    51.5 1916.64    60.1  1915.7    70.9 1912.67
    90.7 1910.05   126.8 1910.54   130.8 1909.76134.72271908.089   138.8 1907.14
   142.8 1907.05150.72271908.001   158.8 1910.12   166.8  1910.9   262.8 1909.88
   364.4 1909.96   410.5 1909.35   568.4 1908.79   629.6 1911.82     642 1910.76
   646.4 1910.81   658.5 1912.71     679 1917.69   691.6 1917.87   695.5 1918.39
     704 1921.34   712.2 1925.73   732.9 1930.52   753.6 1932.44   766.6    1933
#Mann= 8, -1 ,  0
       0    0.08       0      50    0.07       0134.7227   0.045       0
150.7227    0.07       0  150.93    0.06       0  250.93    0.08       0
  346.87    0.07       0  556.87     0.1       0
#XS Ineff= 2 , 0
                           628.6         1915.02
Permanent Ineff=
       F       F
Bank Sta=134.7227,150.7227
XS Rating Curve= 0 ,0
Exp/Cntr(USF)=0,0
Exp/Cntr=0.3,0.1

Type RM Length L Ch R = 1 ,4508    ,387.2,387.2,387.2
XS GIS Cut Line= 2
2293236.92178612711700.9030434852292470.31243287711840.872299845
#Sta/Elev= 30
       0  1915.6    29.2  1916.6    73.9 1910.46    94.3 1909.34   118.7 1911.34
   130.9 1911.11   134.9 1910.72   141.9 1908.49   147.1 1907.53   152.2 1907.47
     159 1908.66   163.4 1909.99   167.5 1910.45   286.3 1908.76   313.8 1909.53
   407.4 1908.37   452.1 1908.98   606.6 1908.76   655.4 1908.26   663.5 1906.48
   667.6 1907.46   675.7    1912   683.9 1912.59   700.1 1911.87   704.2 1912.98
   708.3  1915.3   712.3 1916.19   720.5 1915.61   732.7 1916.45   779.3 1923.56
#Mann= 7, -1 ,  0
       0    0.08       0      80    0.05       0   141.9   0.045       0
     159    0.05       0     380    0.07       0     580     0.1       0
     690    0.07       0
Bank Sta=141.9,159
XS Rating Curve= 0 ,0
Exp/Cntr(USF)=0,0
Exp/Cntr=0.3,0.1

Type RM Length L Ch R = 1 ,4121    ,242.3,242.3,242.3
XS GIS Cut Line= 2
2293415.83454275711423.4565541612292359.27565533 711639.50799687
#Sta/Elev= 30
       0  1915.9    48.6 1916.72    84.6 1915.84   109.9 1912.96   126.2 1910.09
   150.7 1908.97   297.7 1909.34   371.2 1908.68   424.3 1909.89   473.3 1908.74
   530.4 1909.65   536.7 1908.51   543.5 1906.72   550.8 1907.17   557.1 1908.52
   563.1 1909.62   665.1 1908.01   718.2 1909.13   881.5 1908.21   897.9 1905.93
     906  1908.8   909.6 1909.26   926.5 1909.47   930.5 1910.93   938.7 1920.15
   991.8 1935.87  1020.3 1946.47  1058.7  1955.6  1069.3 1957.69  1078.4 1958.21
#Mann= 9, -1 ,  0
       0    0.08       0      70    0.07       0     170   0.055       0
     270    0.05       0   536.7   0.045       0   557.1    0.05       0
     770     0.1       0     870    0.07       0     970     0.1       0
Bank Sta=536.7,557.1
XS Rating Curve= 0 ,0
Exp/Cntr(USF)=0,0
Exp/Cntr=0.3,0.1

Type RM Length L Ch R = 1 ,3878    ,712.1,712.1,712.1
XS GIS Cut Line= 3
2293431.19292514 711358.945888822293050.43424565711299.805311649
2292333.28076392711492.537973086
#Sta/Elev= 30
       0 1916.71    43.5 1916.07      80 1909.57    88.1  1908.6   152.8 1908.78
     165 1908.34   185.2 1908.91   241.9 1908.88   355.2 1907.98   375.5 1908.53
   407.9 1908.21   511.9 1908.92   532.6 1907.07   542.21908.977   598.9 1907.92
   648.6 1908.62   760.5 1908.06   810.1 1908.45   900.8 1907.04   949.8 1907.49
   959.3 1906.23   967.5 1909.31   988.2 1909.59   992.4 1911.99   996.5 1916.27
  1000.7 1919.17  1017.2 1923.98  1054.5 1930.83  1073.9 1932.46  1127.9 1932.15
#Mann= 10, -1 ,  0
       0    0.08       0      80    0.06       0     180    0.05       0
     280   0.055       0  485.32    0.05       0   511.9   0.045       0
   542.2    0.05       0  685.32     0.1       0  895.32    0.07       0
  995.32     0.1       0
Bank Sta=511.9,542.2
XS Rating Curve= 0 ,0
Exp/Cntr(USF)=0,0
Exp/Cntr=0.3,0.1

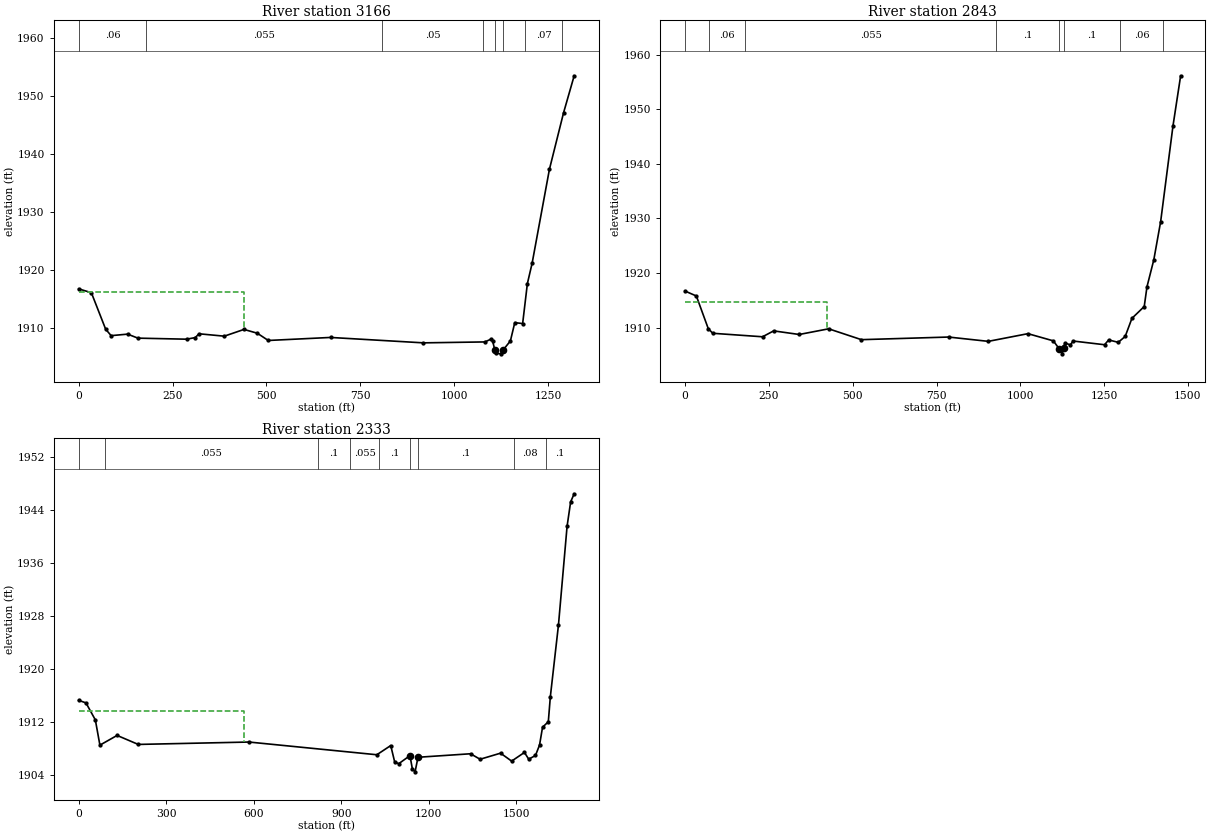
Type RM Length L Ch R = 1 ,3166    ,322.9,322.9,322.9
XS GIS Cut Line= 3
2293448.77335333711318.8779258672292992.26391425711053.436849248
2292237.28834001 711291.29185297
#Sta/Elev= 30
       0 1916.82    33.9 1916.16    71.9 1909.89    86.5 1908.77   130.4 1909.03
     158 1908.34   287.6 1908.16   310.7 1908.44   320.6 1909.09   387.9 1908.68
   440.3 1909.84   475.7 1909.19     505 1907.94   670.8 1908.46   918.2 1907.53
  1081.7 1907.69  1098.5 1908.18  1102.7 1907.78  1108.4 1906.27  1111.5 1905.77
  1123.7 1905.64  1130.7 1906.33  1149.8 1907.86  1161.4 1911.01  1182.4 1910.85
    1195 1917.73  1207.6 1921.22  1253.7 1937.39  1291.4 1947.13  1319.6 1953.48
#Mann= 8, -1 ,  0
       0    0.06       0     180   0.055       0  808.07    0.05       0
 1078.07     0.1       0  1108.4   0.045       0  1130.7    0.06       0
 1188.07    0.07       0 1288.07     0.1       0
#XS Ineff= 2 , 0
          440.02 1916.31
Permanent Ineff=
       F       F
Bank Sta=1108.4,1130.7
XS Rating Curve= 0 ,0
Exp/Cntr(USF)=0,0
Exp/Cntr=0.3,0.1

Type RM Length L Ch R = 1 ,2843    ,510.4,510.4,510.4
XS GIS Cut Line= 3
2293514.44755185711200.9606647852292913.56287765710913.143697047
2292117.72389495711074.266387375
#Sta/Elev= 30
       0 1916.68    33.6 1915.78      69 1909.81    82.4 1908.94     231  1908.3
   264.2 1909.38   340.4 1908.72   428.3 1909.76   525.9 1907.77     786 1908.25
   904.4 1907.46  1022.7 1908.87  1098.5 1907.55  1115.5 1906.13  1124.8 1905.17
  1128.8 1906.21  1132.9 1907.15  1149.3 1906.82  1157.4 1907.52  1251.3 1906.84
  1263.5 1907.72  1292.1 1907.28  1312.8 1908.36  1332.9 1911.68  1369.6 1913.85
  1377.8 1917.47  1398.2 1922.43  1418.6 1929.43  1455.3 1946.95  1478.2 1956.17
#Mann= 8, -1 ,  0
       0    0.08       0      70    0.06       0     180   0.055       0
  926.26     0.1       0  1115.5   0.045       0  1128.8     0.1       0
 1296.26    0.06       0 1426.26     0.1       0
#XS Ineff= 2 , 0
          423.29 1914.74
Permanent Ineff=
       F       F
Bank Sta=1115.5,1128.8
XS Rating Curve= 0 ,0
Exp/Cntr(USF)=0,0
Exp/Cntr=0.3,0.1

Type RM Length L Ch R = 1 ,2333    ,,,
XS GIS Cut Line= 3
 2293631.8381222711003.1294958812292674.03798365710649.666313645
2292089.77071444 710991.93817665
#Sta/Elev= 30
       0 1915.27    25.2 1914.88    57.3 1912.31    72.9  1908.5   131.8 1909.97
   204.3 1908.61   583.8 1908.97  1021.9 1907.05  1069.5 1908.44  1083.3 1905.91
  1097.3 1905.71  1135.31906.918  1143.6 1904.93  1152.9 1904.47  1162.9 1906.67
    1343  1907.2  1375.7 1906.37  1445.8 1907.29  1483.8 1906.09  1527.7  1907.4
  1542.3 1906.38  1565.5 1906.94  1579.4 1908.51  1589.7  1911.2  1609.5 1912.04
  1616.5 1915.84  1644.3 1926.66  1673.8 1941.55    1686 1945.24  1698.1 1946.46
#Mann= 9, -1 ,  0
       0    0.07       0      90   0.055       0     820     0.1       0
     930   0.055       0 1030.94     0.1       0  1135.3   0.045       0
  1162.9     0.1       0 1490.94    0.08       0 1600.94     0.1       0
#XS Ineff= 2 , 0
          565.74 1913.59
Permanent Ineff=
       F       F
Bank Sta=1135.3,1162.9
XS Rating Curve= 0 ,0
Exp/Cntr(USF)=0,0
Exp/Cntr=0.3,0.1
LCMann Table=0

Chan Stop Cuts=-1
Use User Specified Reach Order=0
Composite Channel Slope=5